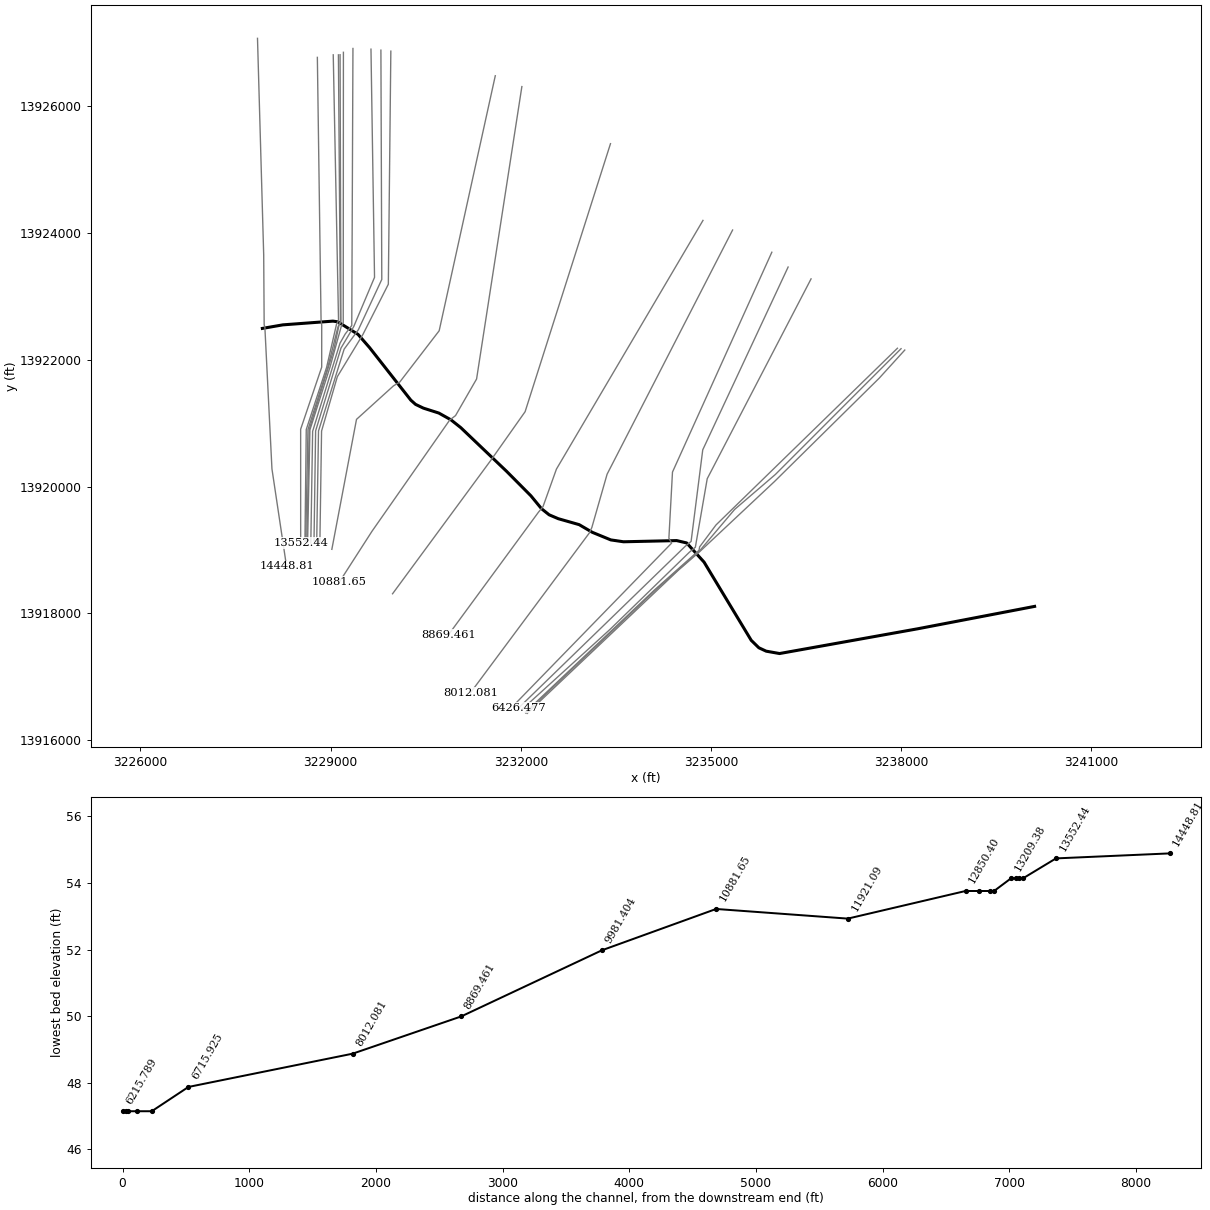
--- Q130-00-00.prj (project) ---

Proj Title=Q130-00-00
Current Plan=p06
Default Exp/Contr=.3,.1
English Units
Geom File=g02
Flow File=f01
Flow File=f04
Plan File=p04
Plan File=p06
Y Axis Title=Elevation
X Axis Title(PF)=Main Channel Distance
X Axis Title(XS)=Station
BEGIN DESCRIPTION:
HCFCD Unit Q130-00-00
Flood Hazard and Floodway Model
10, 2, 1, & 0.2% Events
Filename: Q130.prj
Prepared by: Costello, Inc. Date: August 21, 2003
Reviewed by: _________ Date:____________
Status: Final
END DESCRIPTION:
DSS Export Rating Curves= 0
DSS Export Rating Curve Sorted= 0
DSS Export Volume Flow Curves= 0
DXF OffsetX= 0
DXF OffsetY= 0
DXF ScaleX= 1
DXF ScaleY= 10

--- Q130-00-00.p06 (plan) ---

Plan Title=Floodway
Version=Version 3.0.1  Mar 2001
Short Identifier=Floodway0607
Geom File=g02
Flow File=f04
Subcritical Flow
K Sum by GR= 0
Std Step Tol= 0.01
Critical Tol= 0.01
Num of Std Step Trials= 20
Max Error Tol= 0.3
Flow Tol Ratio= 0.001
Split Flow NTrial= 30
Split Flow Tol= 0.02
Split Flow Ratio= 0.02
Log Output Level= 0
Friction Slope Method= 1
Unsteady Friction Slope Method= 2
Parabolic Critical Depth
Global Vel Dist= 0 , 0 , 0
Global Log Level= 0
CheckData=True
Encroach Param=-1 ,0,0, 2
Encroach River=Q130-00-00
Encroach Reach=Q130-00-00_0001
Encroach Node=14448.81
       1    4400    4800
Encroach Node=13552.44
       1    4000    4400
Encroach Node=13291.94
       1    4000    4400
Encroach Node=13257.21
       1    4000    4400
Encroach Node=13255
       1    4000    4400
Encroach Node=13249.37
       1    4000    4400
Encroach Node=13209.38
       1    4150    4400
Encroach Node=13075.88
       1    4300    4550
Encroach Node=13040.28
       1    4400    4650
Encroach Node=12988
       1    4400    4650
Encroach Node=12953.84
       1    4450    4650
Encroach Node=12850.40
       1    4550    4680
Encroach Node=11921.09
       1    4920    5450
Encroach Node=10881.65
       1 5403.65    6200
Encroach Node=9981.404
       1 5285.82    6000
Encroach Node=8869.461
       1 5184.65    5400
Encroach Node=8012.081
       1    5000    5500
Encroach Node=6715.925
       1    4800    5000
Encroach Node=6426.477
       1 4662.07 4734.47
Encroach Node=6312.756
       1 4668.55 4745.31
Encroach Node=6238.373
       1 4510.74  4602.7
Encroach Node=6226.117
       1 4510.05 4657.58
Encroach Node=6220
       1 4510.05  4675.2
Encroach Node=6215.789
       1 4521.12  4675.2
Encroach Node=6205.579
       1 4488.66 4687.01
Encroach Node=6127
       1 4488.66 4687.01
Encroach Node=6052.988
       1 4556.52 4649.17
Encroach Node=5929.818
       1    4455 4551.89
Encroach Node=5877.368
       1  4537.1 4642.69
Encroach Node=5784
       1    4700    4800
Encroach Node=5686.730
       1 4997.24 5126.42
Encroach Node=5582.118
       1  5058.7 5153.18
Encroach Node=4768.003
       1 5453.15 5549.71
Encroach Node=3750.870
       1 5200.15  5283.1
Encroach Node=2694.539
       1 4459.74 4609.26
Encroach Node=1769.650
       1 3890.93  3989.3
Encroach Node=814.831
       1 3331.24 3445.69
Encroach Node=102.136
       1 3246.62 3337.84
Computation Interval=1HOUR
Output Interval=1HOUR
Run HTab= 0
Run UNet= 0
Run PostProcess= 0
UNET Theta= 1
UNET ZTol= 0.02
UNET ZSATol= 0.1
UNET MxIter= 20
UNET MaxInSteps= 20
UNET DtIC= 0
UNET DtMin= 0
UNET MaxCRTS= 20
UNET WFStab= 2
UNET SFStab= 1
UNET WFX= 1
UNET SFX= 1
UNET Convert EG Bridges=-1
UNET Use Existing IB Tables=-1
Instantaneous Interval=1HOUR
Write IC File= 0
Write Velocity= 0
Write Detailed= 0

--- Q130-00-00.p04 (plan) ---

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Plan Title=FEMA Effective June 2007
Short Identifier=FEMAeff0607
Geom File=g02
Flow File=f01
Encroach Param=-1 ,0,0, 0

--- Q130-00-00.f04 (steady flow) ---

Flow Title=Floodway
Version=Version 3.0.1  Mar 2001
Number of Profiles= 2
Profile Names=1PCT_100yr,1PCTFloodway_100yrFW
River Rch & RM=Q130-00-00,Q130-00-00_0001 ,14448.81
     618     618
River Rch & RM=Q130-00-00,Q130-00-00_0001 ,13552.44
     665     665
River Rch & RM=Q130-00-00,Q130-00-00_0001 ,13291.94
     681     681
River Rch & RM=Q130-00-00,Q130-00-00_0001 ,13209.38
     714     714
River Rch & RM=Q130-00-00,Q130-00-00_0001 ,13040.28
     720     720
River Rch & RM=Q130-00-00,Q130-00-00_0001 ,12850.40
     752     752
River Rch & RM=Q130-00-00,Q130-00-00_0001 ,11921.09
     789     789
River Rch & RM=Q130-00-00,Q130-00-00_0001 ,10881.65
     823     823
River Rch & RM=Q130-00-00,Q130-00-00_0001 ,9981.404
     867     867
River Rch & RM=Q130-00-00,Q130-00-00_0001 ,8869.461
     902     902
River Rch & RM=Q130-00-00,Q130-00-00_0001 ,8012.081
    1047    1047
River Rch & RM=Q130-00-00,Q130-00-00_0001 ,6715.925
    1096    1096
River Rch & RM=Q130-00-00,Q130-00-00_0001 ,6312.756
    1262    1262
River Rch & RM=Q130-00-00,Q130-00-00_0001 ,6238.373
    1317    1317
River Rch & RM=Q130-00-00,Q130-00-00_0001 ,6215.789
    1343    1343
River Rch & RM=Q130-00-00,Q130-00-00_0001 ,6205.579
    1376    1376
River Rch & RM=Q130-00-00,Q130-00-00_0001 ,5582.118
    1420    1420
River Rch & RM=Q130-00-00,Q130-00-00_0001 ,4768.003
    1478    1478
River Rch & RM=Q130-00-00,Q130-00-00_0001 ,3750.870
    1540    1540
River Rch & RM=Q130-00-00,Q130-00-00_0001 ,2694.539
    1597    1597
River Rch & RM=Q130-00-00,Q130-00-00_0001 ,1769.650
    1658    1658
River Rch & RM=Q130-00-00,Q130-00-00_0001 ,814.831
    1705    1705
Boundary for River Rch & Prof#=Q130-00-00,Q130-00-00_0001 , 1
Up Type= 0
Dn Type= 3
Dn Slope=.0055
Boundary for River Rch & Prof#=Q130-00-00,Q130-00-00_0001 , 2
Up Type= 0
Dn Type= 3
Dn Slope=.0055
DSS Import GetInterval= 0
DSS Import GetPeak= 0
DSS Import FillOption= 0

--- Q130-00-00.f01 (steady flow) ---

Flow Title=FEMA Effective June 2007
Version=Version 3.0.1  Mar 2001
Number of Profiles= 4
Profile Names=10PCT_10yr,2PCT_50yr,1PCT_100yr,0.2PCT_500yr
River Rch & RM=Q130-00-00,Q130-00-00_0001 ,14448.81
     338     522     618     904
River Rch & RM=Q130-00-00,Q130-00-00_0001 ,13552.44
     363     561     665     975
River Rch & RM=Q130-00-00,Q130-00-00_0001 ,13291.94
     371     574     681     998
River Rch & RM=Q130-00-00,Q130-00-00_0001 ,13209.38
     389     601     714    1048
River Rch & RM=Q130-00-00,Q130-00-00_0001 ,13040.28
     392     606     720    1058
River Rch & RM=Q130-00-00,Q130-00-00_0001 ,12850.40
     409     633     752    1106
River Rch & RM=Q130-00-00,Q130-00-00_0001 ,11921.09
     429     663     789    1162
River Rch & RM=Q130-00-00,Q130-00-00_0001 ,10881.65
     447     691     823    1213
River Rch & RM=Q130-00-00,Q130-00-00_0001 ,9981.404
     470     727     867    1279
River Rch & RM=Q130-00-00,Q130-00-00_0001 ,8869.461
     489     756     902    1333
River Rch & RM=Q130-00-00,Q130-00-00_0001 ,8012.081
     566     875    1047    1553
River Rch & RM=Q130-00-00,Q130-00-00_0001 ,6715.925
     592     916    1096    1629
River Rch & RM=Q130-00-00,Q130-00-00_0001 ,6312.756
     680    1051    1262    1882
River Rch & RM=Q130-00-00,Q130-00-00_0001 ,6238.373
     709    1096    1317    1967
River Rch & RM=Q130-00-00,Q130-00-00_0001 ,6205.579
     743    1147    1376    2037
River Rch & RM=Q130-00-00,Q130-00-00_0001 ,5582.118
     772    1186    1420    2079
River Rch & RM=Q130-00-00,Q130-00-00_0001 ,4768.003
     809    1237    1478    2132
River Rch & RM=Q130-00-00,Q130-00-00_0001 ,3750.870
     849    1292    1540    2188
River Rch & RM=Q130-00-00,Q130-00-00_0001 ,2694.539
     886    1342    1597    2239
River Rch & RM=Q130-00-00,Q130-00-00_0001 ,1769.650
     925    1396    1658    2292
River Rch & RM=Q130-00-00,Q130-00-00_0001 ,814.831
     956    1437    1705    2333
Boundary for River Rch & Prof#=Q130-00-00,Q130-00-00_0001 , 1
Up Type= 0
Dn Type= 3
Dn Slope=.0055
Boundary for River Rch & Prof#=Q130-00-00,Q130-00-00_0001 , 2
Up Type= 0
Dn Type= 3
Dn Slope=.0055
Boundary for River Rch & Prof#=Q130-00-00,Q130-00-00_0001 , 3
Up Type= 0
Dn Type= 3
Dn Slope=.0055
Boundary for River Rch & Prof#=Q130-00-00,Q130-00-00_0001 , 4
Up Type= 0
Dn Type= 3
Dn Slope=.0055
DSS Import GetInterval= 0
DSS Import GetPeak= 0
DSS Import FillOption= 0

--- Q130-00-00.g02 (geometry) ---

Geom Title=Q130-00-00 June 2007
Version=Version 3.0.1  Mar 2001

River Reach=Q130-00-00      ,Q130-00-00_0001
Reach XY= 30
     3227923.365     13922494.97     3228247.097    13922551.155
      3229036.36    13922610.015     3229113.949    13922599.313
      3229432.33    13922401.328     3229614.261    13922192.642
     3230265.738    13921363.246     3230340.651     13921296.36
     3230463.723    13921237.499      3230707.19    13921159.911
     3230898.486    13921052.892     3231053.664    13920929.821
     3231777.378     13920239.55      3232159.97    13919854.282
     3232327.187    13919650.947     3232447.583     13919554.63
     3232592.058    13919493.094     3232921.141    13919399.452
     3233127.152    13919279.056     3233420.116     13919158.66
     3233620.776     13919129.23     3234459.535    13919147.958
     3234617.388    13919110.502     3234891.623    13918808.174
     3235635.404    13917574.783       3235755.8    13917457.062
     3235870.845    13917403.553     3236082.207    13917366.096
     3238262.714    13917756.715     3240106.112    13918109.877

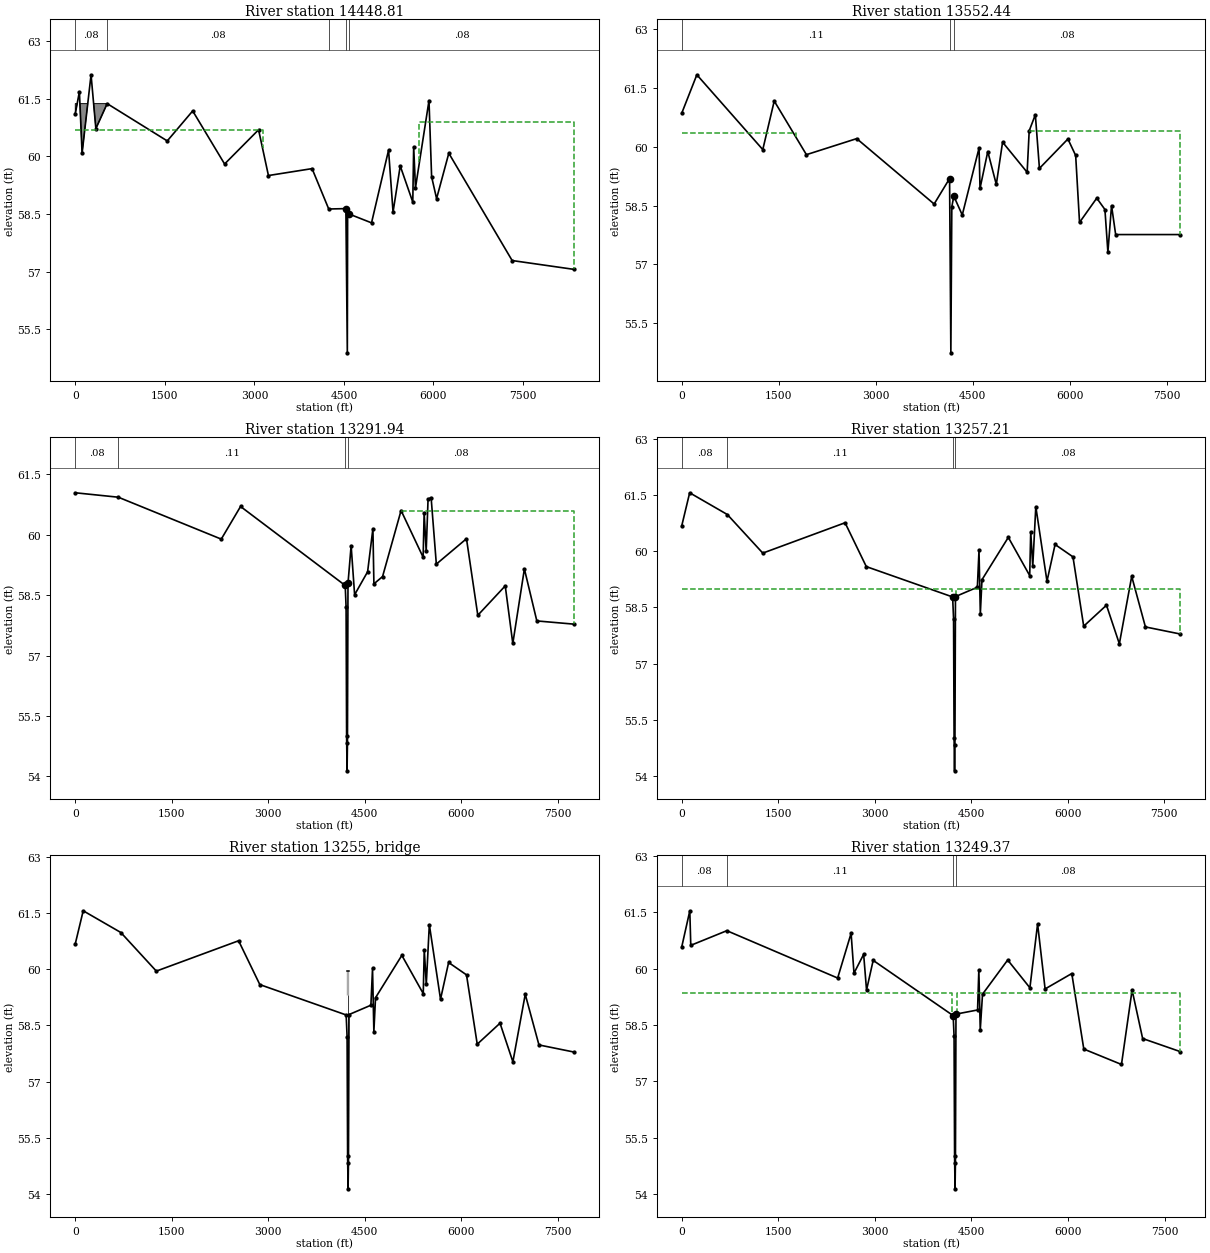
Type RM Length L Ch R = 1 ,14448.81,896.36,896.36,896.36
BEGIN DESCRIPTION:
K
END DESCRIPTION:
XS GIS Cut Line= 6
      3227846.71    13927071.179     3227944.622     13923653.05
     3227951.923    13922553.257     3227963.207    13922512.412
     3228074.675    13920279.741     3228304.983    13918740.434
#Sta/Elev= 30
       0   61.11   68.86   61.68  113.88   60.08  263.94   62.12   344.6   60.72
  534.05   61.37 1540.47    60.4 1966.53   61.18 2500.86    59.8 3070.09   60.69
 3235.16    59.5 3966.12   59.68 4245.18   58.63 4532.36   58.64 4556.66   54.89
 4561.72   58.48 4585.47    58.5 4962.01   58.27  5247.4   60.16 5322.51   58.55
 5442.68   59.75 5652.99   58.81 5668.01   60.25 5698.05   59.18 5924.58   61.45
 5968.44   59.47 6051.64    58.9 6256.49   60.08 7317.49   57.29 8353.69   57.06
#Mann= 5 ,-1 , 0
       0     .08       0  534.05     .08       0 4245.18     .11       0
 4532.36     .05       0 4585.47     .08       0
#XS Ineff= 2 , 0
       0 3136.44   60.69 5764.58       0   60.89
Permanent Ineff=
       F       F
#Block Obstruct= 2 , 0
       0  534.05   61.37 5924.58       0   61.45
Bank Sta=4532.36,4585.47
XS Rating Curve= 0
Exp/Cntr=.3,.1

Type RM Length L Ch R = 1 ,13552.44,260.51,260.51,260.51
XS GIS Cut Line= 6
     3228791.089     13926770.85     3228849.356    13922635.628
     3228859.912    13922546.073     3228859.391    13921883.561
     3228527.472    13920904.294     3228527.862    13919110.709
#Sta/Elev= 30
       0   60.86  233.53   61.84 1253.63   59.93 1430.68   61.17 1928.69    59.8
 2706.74   60.21 3904.68   58.54 4143.44   59.19 4163.32   54.74 4178.16   58.47
 4209.17   58.74 4339.78   58.26 4599.53   59.97 4614.53   58.94 4734.53   59.88
  4866.5   59.04 4963.47   60.12 5343.63   59.35 5375.31   60.41 5470.34   60.82
 5533.69   59.45 5974.26    60.2 6094.26   59.78 6154.26   58.07 6420.62   58.69
 6546.83    58.4 6592.91   57.31 6649.26    58.5 6713.09   57.76 7715.89   57.76
#Mann= 3 ,-1 , 0
       0     .11       0 4143.44     .05       0 4209.17     .08       0
#XS Ineff= 2 , 0
       0 1765.13   60.36 5375.31       0   60.41
Permanent Ineff=
       F       F
#Block Obstruct= 2 , 0
       0                 5470.34       0   60.82
Bank Sta=4143.44,4209.17
XS Rating Curve= 0
Exp/Cntr=.3,.1

Type RM Length L Ch R = 1 ,13291.94,34.73,34.73,34.73
XS GIS Cut Line= 6
     3229041.717     13926810.95     3229125.069    13922622.284
     3229093.519    13922561.159     3228937.131     13921881.05
     3228616.071    13920900.094     3228595.222    13919135.969
#Sta/Elev= 30
       0   61.04  668.81   60.93 2269.05   59.89 2569.11    60.7 4195.91   58.74
  4209.5    58.2 4217.56   55.01 4224.75   54.14 4230.66   54.84 4239.08   58.79
 4287.85   59.73    4342   58.51 4544.08   59.08 4626.46   60.15 4641.85   58.78
 4776.33   58.96  5064.3    60.6 5407.22   59.44    5423   60.55 5454.57   59.59
 5483.72   60.88 5531.29   60.92  5612.4   59.27 6081.05    59.9 6257.04      58
 6683.56   58.73  6801.1    57.3 6981.12   59.15  7174.6   57.86 7752.55   57.78
#Mann= 4 ,-1 , 0
       0     .08       0  668.81     .11       0 4195.91     .05       0
 4239.08     .08       0
#XS Ineff= 2 , 0
       0 2797.69   60.39  5064.3       0    60.6
Permanent Ineff=
       F       F
#Block Obstruct= 2 , 0
       0                 5531.29       0   60.92
Bank Sta=4195.91,4239.08
XS Rating Curve= 0
Exp/Cntr=.5,.3

Type RM Length L Ch R = 1 ,13257.21,20,20,20
XS GIS Cut Line= 6
     3229123.274    13926810.302     3229155.761    13922606.187
       3229116.3    13922516.994     3228954.468     13921878.05
     3228642.962    13920899.931     3228606.585    13919137.568
#Sta/Elev= 30
       0   60.68  122.96   61.56  708.01   60.98 1259.38   59.95 2538.06   60.76
 2868.07   59.59 4209.69   58.78 4224.33    58.2 4232.39   55.01 4239.58   54.14
 4245.49   54.84 4253.91   58.79 4594.21   59.04 4619.59   60.02 4640.31   58.33
 4665.99   59.24 5075.22   60.37 5407.75   59.35  5423.5   60.52 5455.01    59.6
 5502.43   61.19 5676.21    59.2 5802.12   60.18 6080.04   59.85 6246.91      58
  6600.9   58.56 6800.95   57.53  6992.9   59.33 7206.06   57.98 7750.93   57.79
#Mann= 4 ,-1 , 0
       0     .08       0  708.01     .11       0 4209.69    .049       0
 4253.91     .08       0
#XS Ineff= 2 , 0
       0 4200.75      59 4263.91       0      59
Permanent Ineff=
       F       F
#Block Obstruct= 2 , 0
       0                 5502.43       0   61.19
Bank Sta=4209.69,4253.91
XS Rating Curve= 0
Exp/Cntr=.5,.3

Type RM Length L Ch R = 3 ,13255   ,,,
BEGIN DESCRIPTION:
PED BRIDGE U/S OF DAIRY OAK
END DESCRIPTION:
Bridge Culvert--1,0,-1,-1, 0
Deck Dist Width WeirC Skew NumUp NumDn MinLoCord MaxHiCord MaxSubmerge Is_Ogee
6,4,2.6,0, 4, 4, , , .95, 0, 0,0,,
    4219    4220    4255    4256
   59.96   59.96   59.96   59.96
      58    59.3    59.3      58
    4226    4227    4262    4263
   59.96   59.96   59.96   59.96
      58    59.3    59.3      58
Pier Skew, UpSta & Num, DnSta & Num=  ,4238, 2 ,4245, 2 , 0 , 0 , 0 ,,
     .35     .35
      50      60
     .35     .35
      50      60
BR Coef=-1 , 1 , 1 ,1.05, 0 ,,,.8,-1,1.2,0,
WSPro=,,,, 1 ,,,, 0 ,,,, 0 ,,,,-1 ,-1 ,-1 , 0 , 0 , 0 , 0 , 0
BR U #Sta/Elev= 30
       0   60.68  122.96   61.56  708.01   60.98 1259.38   59.95 2538.06   60.76
 2868.07   59.59 4209.69   58.78 4224.33    58.2 4232.39   55.01 4239.58   54.14
 4245.49   54.84 4253.91   58.79 4594.21   59.04 4619.59   60.02 4640.31   58.33
 4665.99   59.24 5075.22   60.37 5407.75   59.35  5423.5   60.52 5455.01    59.6
 5502.43   61.19 5676.21    59.2 5802.12   60.18 6080.04   59.85 6246.91      58
  6600.9   58.56 6800.95   57.53  6992.9   59.33 7206.06   57.98 7750.93   57.79
BR U #Mann= 4
       0     .08  708.01     .11 4209.69    .049 4253.91     .08
BC Design=,, 0 ,, 0 ,,,,,,

Type RM Length L Ch R = 1 ,13249.37,39.99,39.99,39.99
XS GIS Cut Line= 6
     3229149.399    13926812.374     3229162.874    13922602.902
     3229131.324    13922541.776      3229053.91     13922173.04
     3228663.623    13920902.903     3228624.416    13919141.134
#Sta/Elev= 30
       0   60.58  125.03   61.54  140.03   60.62  700.15   61.01  2421.4   59.75
 2630.12   60.94 2675.12   59.88 2825.12   60.38 2870.12   59.43 2973.04   60.22
 4215.71   58.75  4229.6    58.2 4237.65   55.01 4244.84   54.14 4250.75   54.84
 4259.17   58.79 4594.55    58.9 4614.31   59.97 4636.29   58.37 4671.51   59.32
 5062.36   60.23  5407.4   59.49 5526.98   61.19 5643.45   59.46 6057.89   59.87
  6244.6   57.86 6829.75   57.45 6994.79   59.43 7158.42   58.14 7746.18   57.79
#Mann= 4 ,-1 , 0
       0     .08       0  700.15     .11       0 4215.71    .049       0
 4259.17     .08       0
#XS Ineff= 2 , 0
       0 4200.92   59.35 4271.17       0   59.35
Permanent Ineff=
       F       F
#Block Obstruct= 2 , 0
       0                 5526.98       0   61.19
Bank Sta=4215.71,4259.17
XS Rating Curve= 0
Exp/Cntr=.5,.3

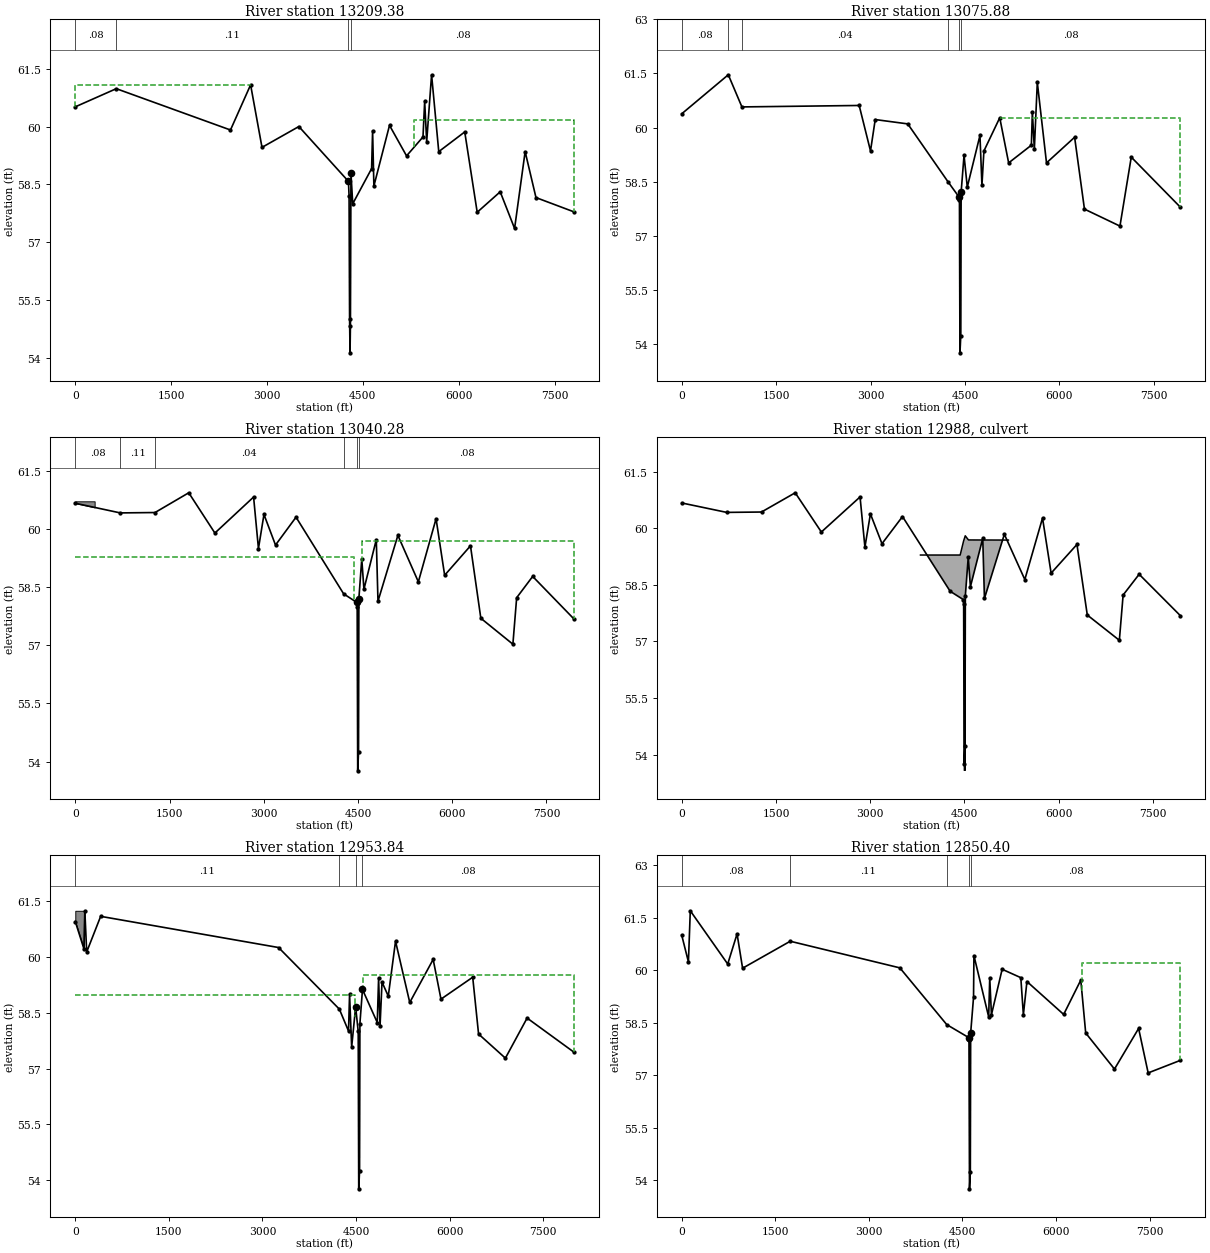
Type RM Length L Ch R = 1 ,13209.38,133.5,133.5,133.5
XS GIS Cut Line= 6
     3229202.119    13926851.051     3229199.313    13922586.403
     3229167.763    13922525.277     3228990.028    13921883.521
     3228673.817    13920894.842     3228637.322    13919127.549
#Sta/Elev= 30
       0   60.51  641.55   60.98  2428.7   59.91  2743.7   61.08 2921.96   59.46
 3498.95      60 4275.05   58.58 4284.66    58.2 4292.71   55.01  4299.9   54.14
 4305.81   54.84 4314.23   58.79 4341.87      58 4637.39   58.91 4652.96   59.89
 4673.09   58.46 4917.56   60.03 5184.31   59.24 5441.55   59.73 5467.79   60.65
 5499.28   59.61 5575.95   61.34 5688.27   59.35 6094.87   59.86 6289.91   57.78
 6649.99   58.31 6875.04   57.36 7040.07   59.35 7209.76   58.16 7805.04   57.79
#Mann= 4 ,-1 , 0
       0     .08       0  641.55     .11       0 4275.05     .05       0
 4314.23     .08       0
#XS Ineff= 2 , 0
       0  2743.7   61.08 5298.36       0   60.17
Permanent Ineff=
       F       F
#Block Obstruct= 2 , 0
       0                 5588.19       0   61.25
Bank Sta=4275.05,4314.23
XS Rating Curve= 0
Exp/Cntr=.3,.1

Type RM Length L Ch R = 1 ,13075.88,35.61,35.61,35.61
BEGIN DESCRIPTION:
J
END DESCRIPTION:
XS GIS Cut Line= 6
     3229352.495    13926911.201     3229333.816    13922540.804
     3229230.831     13922407.56     3229148.115     13922261.33
     3228716.573    13920872.012     3228687.842    13919110.709
#Sta/Elev= 30
       0   60.38  739.35   61.46  955.77   60.57 2818.88   60.61 2998.88   59.35
 3073.88   60.22 3590.72    60.1 4232.98   58.49  4407.4   58.07 4411.91      58
 4420.12   53.76 4433.52   54.24 4438.87   58.21 4484.92   59.23 4536.37   58.35
 4737.89   59.78 4769.33    58.4 4800.78   59.35 5052.35   60.27 5193.76   59.02
 5554.88   59.51 5570.58   60.44 5601.98    59.4 5649.08   61.25 5795.27   59.02
  6241.9   59.73 6398.21   57.74 6962.08   57.27 7141.82   59.18 7923.85   57.79
#Mann= 6 ,-1 , 0
       0     .08       0  739.35     .11       0  955.77     .04       0
 4232.98     .08       0  4407.4     .05       0 4438.87     .08       0
#XS Ineff= 2 , 0
       0 3590.72    60.1 5052.35       0   60.27
Permanent Ineff=
       F       F
#Block Obstruct= 2 , 0
       0                 5052.35       0   60.27
Bank Sta=4407.4,4438.87
XS Rating Curve= 0
Exp/Cntr=.5,.3

Type RM Length L Ch R = 1 ,13040.28,86.43,86.43,86.43
XS GIS Cut Line= 6
     3229636.958     13926900.55     3229693.049    13923300.551
     3229364.106    13922522.206     3229163.365    13922183.987
     3228763.645    13920878.895     3228738.361    13919144.389
#Sta/Elev= 30
       0   60.67  715.84   60.42 1269.44   60.43 1806.04   60.94 2222.33    59.9
 2838.38   60.83 2915.73    59.5 3003.38   60.38 3187.37   59.59 3513.98   60.31
 4272.08   58.33 4480.63   58.11 4487.41      58 4495.62   53.76 4509.02   54.24
 4514.37   58.21 4560.42   59.23 4594.99   58.45 4791.56   59.73  4818.5   58.14
 5135.32   59.84 5461.24   58.64 5743.15   60.27 5879.89   58.81 6291.03   59.57
 6455.79    57.7  6966.1   57.03 7026.11   58.23 7281.13   58.78 7939.17   57.68
#Mann= 6 ,-1 , 0
       0     .08       0  715.84     .11       0 1269.44     .04       0
 4272.08     .08       0 4480.63     .05       0 4514.37     .08       0
#XS Ineff= 2 , 0
       0    4432   59.29    4564       0   59.69
Permanent Ineff=
       F       F
#Block Obstruct= 2 , 0
       0  308.06   60.72 5743.16       0   60.27
Bank Sta=4480.63,4514.37
XS Rating Curve= 0
Exp/Cntr=.5,.3

Type RM Length L Ch R = 2 ,12988   ,,,
BEGIN DESCRIPTION:
CULVERTS  @ DAIRY OAK
END DESCRIPTION:
Bridge Culvert--1,0,-1,-1, 0
Deck Dist Width WeirC Skew NumUp NumDn MinLoCord MaxHiCord MaxSubmerge Is_Ogee
37,30,2.6,0, 6, 6, , , .95, 0, 0,0,,
    3800    4432    4486    4513    4564    5200
   59.29   59.29   59.66    59.8   59.69 59.6866
                                                
    3800    4477    4532    4559    4610    5200
   59.29   59.29   59.66    59.8   59.69 59.6886
                                                
Multiple Barrel Culv=1,4,,30,.024,.5,1,2,1,53.57,53.53, 2,Culvert #1  , 0 ,37
    4501    4547    4506    4552
Culvert Bottom n=.024
BC Design=,, 0 ,, 0 ,,,,,,

Type RM Length L Ch R = 1 ,12953.84,103.45,103.45,103.45
XS GIS Cut Line= 6
       3229793.6    13926884.885     3229807.458    13923267.289
     3229438.054    13922474.301      3229213.23     13922167.34
     3228809.283    13920877.851     3228780.461    13919110.709
#Sta/Elev= 30
       0   60.96  137.54   60.23  152.95   61.25  182.54   60.14  406.55    61.1
 3257.58   60.26 4231.98    58.6 4378.77   58.01 4395.32      59 4428.87   57.58
 4492.45   58.66 4533.93      58 4542.14   53.76 4555.53   54.24 4560.89   58.21
 4602.29   59.13 4839.25   58.24 4860.71   59.44 4883.55   58.14 4915.39   59.33
 5015.78   58.95 5131.88   60.43 5359.76   58.78 5735.12   59.94 5860.24   58.87
 6368.64   59.46 6462.71   57.93 6892.37   57.28 7240.47   58.36 7992.16   57.44
#Mann= 4 ,-1 , 0
       0     .11       0 4231.98     .08       0 4492.45     .05       0
 4602.29     .08       0
#XS Ineff= 2 , 0
       0    4477   58.98    4610       0   59.52
Permanent Ineff=
       F       F
#Block Obstruct= 2 , 0
       0  152.95   61.25 5106.46       0    60.4
Bank Sta=4492.45,4602.29
XS Rating Curve= 0
Exp/Cntr=.5,.3

Type RM Length L Ch R = 1 ,12850.40,929.31,929.31,929.31
XS GIS Cut Line= 6
     3229950.242    13926869.221     3229910.815    13923192.225
     3229510.436    13922401.026     3229106.447    13921734.425
     3228857.523    13920876.089     3228830.981    13919119.129
#Sta/Elev= 30
       0      61  106.88   60.24  136.88    61.7  736.89   60.18  886.89   61.04
  975.47   60.06 1739.34   60.83 3497.16   60.07 4248.78   58.45  4600.6   58.08
 4605.55      58 4613.76   53.76 4627.15   54.24 4632.51   58.21 4678.55   59.23
 4684.86   60.42 4921.25   58.67 4938.37   59.79 4965.45   58.73 5137.18   60.03
 5436.53   59.79  5477.6   58.73 5534.68   59.68 6123.72   58.74 6398.33   59.72
 6476.96   58.21 6938.39   57.18 7325.53   58.34 7478.45   57.07 7996.73   57.43
#Mann= 5 ,-1 , 0
       0     .08       0 1739.34     .11       0 4248.78     .08       0
  4600.6     .05       0 4632.51     .08       0
#XS Ineff= 2 , 0
       0    3400   60.08    6415       0    60.2
Permanent Ineff=
       F       F
#Block Obstruct= 2 , 0
       0                 6398.33       0   59.72
Bank Sta=4600.6,4632.51
XS Rating Curve= 0
Exp/Cntr=.3,.1

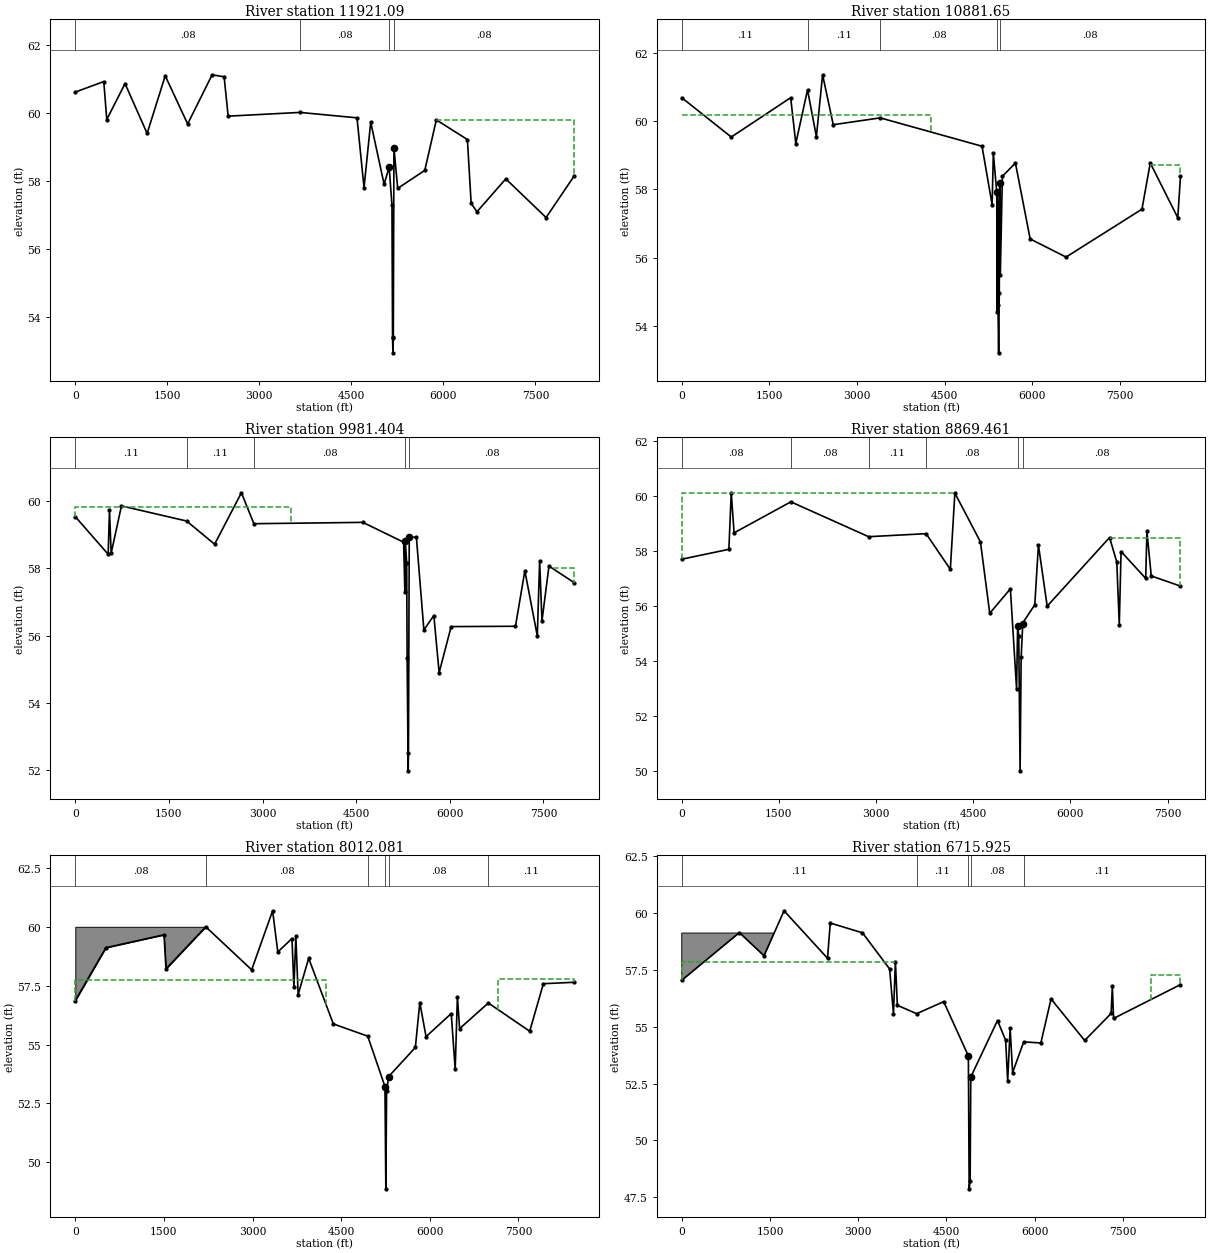
Type RM Length L Ch R = 1 ,11921.09,1062,1039.44,1215
BEGIN DESCRIPTION:
I
END DESCRIPTION:
XS GIS Cut Line= 6
     3231598.034     13926480.92       3230712.7     13922458.09
     3230091.494     13921649.52     3229991.659    13921588.588
     3229408.597    13921060.087     3229019.695     13919009.95
#Sta/Elev= 30
       0   60.62  464.43   60.93  513.14   59.81  810.95   60.87 1170.94    59.4
 1465.92    61.1 1831.37   59.68 2230.71   61.13 2425.92   61.07 2491.81   59.91
 3661.25   60.02 4592.01   59.86 4706.43    57.8 4815.37   59.73 5033.99    57.9
 5116.18   58.41 5161.73   57.29 5171.67   53.36 5177.58   52.93 5183.78    53.4
  5194.1   58.96 5255.71   57.78 5696.58   58.31 5885.12    59.8  6391.5   59.22
 6452.57   57.34 6547.39   57.09 7017.47   58.06 7673.97   56.92 8129.35   58.14
#Mann= 4 ,-1 , 0
       0     .08       0 3661.25     .08       0 5116.18     .05       0
  5194.1     .08       0
#XS Ineff= 2 , 0
       0 4815.37   59.73 5885.12       0    59.8
Permanent Ineff=
       F       F
#Block Obstruct= 2 , 0
       0                  6391.5       0   59.22
Bank Sta=5116.18,5194.1
XS Rating Curve= 0
Exp/Cntr=.3,.1

Type RM Length L Ch R = 1 ,10881.65,900.25,900.25,900.25
BEGIN DESCRIPTION:
H
END DESCRIPTION:
XS GIS Cut Line= 6
     3232017.402    13926310.066     3231302.923    13921697.014
     3230970.745    13921119.696     3230878.273    13921048.503
     3229652.935    13919294.971     3229140.277    13918497.504
#Sta/Elev= 30
       0   60.68  847.71   59.53 1864.69   60.68 1952.48   59.34 2153.09   60.91
 2304.88   59.54 2411.13   61.35 2593.27   59.89 3397.75   60.09 5140.69   59.26
 5313.75   57.55 5334.11   59.06 5392.32   57.92 5400.76   54.42 5403.65   57.93
  5408.2    57.6 5413.97   54.61 5424.94   53.22 5435.97   54.98 5442.85   58.19
 5450.82   58.18 5453.77   55.51 5488.83   58.38  5712.3   58.77 5964.61   56.55
 6578.78   56.02 7878.49   57.42 8020.78   58.77 8491.79   57.17 8538.09   58.38
#Mann= 5 ,-1 , 0
       0     .11       0 2153.09     .11       0 3397.75     .08       0
 5403.65     .05       0 5450.82     .08       0
#XS Ineff= 2 , 0
       0  4272.5   60.16 8013.59       0   58.72
Permanent Ineff=
       F       F
#Block Obstruct= 2 , 0
       0                 8020.78       0   58.77
Bank Sta=5403.65,5450.82
XS Rating Curve= 0
Exp/Cntr=.3,.1

Type RM Length L Ch R = 1 ,9981.404,1111.94,1111.94,1111.94
BEGIN DESCRIPTION:
G
END DESCRIPTION:
XS GIS Cut Line= 6
     3233415.297    13925409.201     3232068.491    13921181.285
     3231579.482     13920487.78     3231548.916    13920444.516
     3231530.415    13920418.327     3229977.395    13918308.865
#Sta/Elev= 30
       0   59.54  526.79   58.42  547.69   59.74  574.55   58.45   739.5   59.86
 1783.37   59.41 2232.16   58.72 2661.29   60.25 2861.86   59.33 4607.61   59.37
 5260.42   58.78 5280.23    57.3 5285.82   58.83 5309.41   58.17 5316.56   55.33
 5333.16   51.98 5337.91   52.51 5350.54   58.94 5465.21   58.92 5584.91   56.17
 5744.61    56.6 5829.37    54.9 6021.86   56.27  7052.4   56.28  7202.6   57.93
 7402.38   55.99 7439.64   58.22 7476.89   56.44 7589.04   58.07 7990.34   57.58
#Mann= 5 ,-1 , 0
       0     .11       0 1783.37     .11       0 2861.86     .08       0
 5285.82     .05       0 5350.54     .08       0
#XS Ineff= 2 , 0
       0 3463.88   59.84 7663.64       0   58.02
Permanent Ineff=
       F       F
#Block Obstruct= 2 , 0
       0                 7663.64       0   58.02
Bank Sta=5285.82,5350.54
XS Rating Curve= 0
Exp/Cntr=.3,.1

Type RM Length L Ch R = 1 ,8869.461,857.38,857.38,857.38
XS GIS Cut Line= 6
     3234874.597    13924199.009     3232562.462    13920275.386
     3232350.106    13919681.785     3232326.012    13919652.631
      3232279.18    13919595.961     3230857.555    13917659.637
#Sta/Elev= 30
       0    57.7  727.37   58.06  763.89   60.12  807.71   58.66 1684.12   59.79
 2884.19   58.52 3771.68   58.63 4145.68   57.33 4215.32   60.11 4610.54   58.33
 4753.91   55.73 5072.53   56.62 5168.12   52.98 5184.65   55.28 5201.46   54.91
 5222.47   49.99 5238.77   54.12 5263.53   55.35  5263.9   55.38 5449.34   56.04
 5505.17   58.22 5640.46   55.99 6603.61   58.49 6714.73    57.6 6753.53   55.32
 6781.03   57.98 7161.34      57 7179.94   58.71 7247.13   57.09 7698.15   56.72
#Mann= 6 ,-1 , 0
       0     .08       0 1684.12     .08       0 2884.19     .11       0
 3771.68     .08       0 5184.65     .05       0  5263.9     .08       0
#XS Ineff= 2 , 0
       0 4215.32   60.11 6603.61       0   58.49
Permanent Ineff=
       F       F
#Block Obstruct= 2 , 0
       0                 6603.61       0   58.49
Bank Sta=5184.65,5263.53
XS Rating Curve= 0
Exp/Cntr=.3,.1

Type RM Length L Ch R = 1 ,8012.081,1296.16,1296.16,1296.16
BEGIN DESCRIPTION:
F
END DESCRIPTION:
XS GIS Cut Line= 6
     3235341.695    13924047.202      3233361.93     13920195.44
     3233120.834    13919352.889     3233110.546    13919330.832
     3233080.663    13919266.769     3231207.878    13916748.796
#Sta/Elev= 30
       0   56.87  517.09   59.12 1501.47   59.67 1534.59   58.22 2208.06   60.01
 2985.01   58.18 3339.18   60.69 3427.42   58.94 3667.11   59.51 3699.92   57.44
 3732.73   59.61 3771.53   57.13 3949.63   58.67 4366.92   55.88  4949.2   55.36
 5240.49   53.22 5255.59   48.87 5268.62   53.04 5302.16   53.64 5755.16   54.88
 5830.57   56.79 5935.99   55.34 6362.39   56.32 6429.32   53.96  6466.7   57.03
 6504.09   55.68 6990.14   56.77  7690.5   55.57 7921.37   57.59 8440.23   57.65
#Mann= 6 ,-1 , 0
       0     .08       0 2208.06     .08       0  4949.2     .08       0
 5240.49     .05       0 5302.16     .08       0 6990.14     .11       0
#XS Ineff= 2 , 0
       0 4249.92   57.76 7158.38       0    57.8
Permanent Ineff=
       F       F
#Block Obstruct= 2 , 0
       0 2208.06   60.01 7921.37       0   57.59
Bank Sta=5240.49,5302.16
XS Rating Curve= 0
Exp/Cntr=.3,.1

Type RM Length L Ch R = 1 ,6715.925,289.45,289.45,289.45
XS GIS Cut Line= 6
       3235960.6    13923696.878     3234393.393    13920228.808
     3234336.641    13919186.409     3234367.038    13919131.276
     3234379.828    13919108.077     3231912.046    13916572.334
#Sta/Elev= 30
       0   57.05  979.53   59.15 1398.33   58.13 1738.81   60.11 2477.62   58.02
 2524.28   59.57 3072.11   59.14    3533   57.55 3598.84   55.58 3631.77   57.87
 3664.69   55.95 3992.48   55.58 4452.13   56.11 4871.88   53.72 4885.57   47.87
 4902.19   48.22 4912.64   52.79 5367.14   55.28 5505.75   54.41 5540.17   52.61
 5582.03   54.94 5623.89   52.99 5813.06   54.34 6104.05   54.29 6277.16   56.23
 6848.83    54.4 7298.36   55.59 7319.29   56.79 7340.08   55.37 8477.48   56.86
#Mann= 5 ,-1 , 0
       0     .11       0 3992.48     .11       0 4871.88     .05       0
 4912.64     .08       0 5813.06     .11       0
#XS Ineff= 2 , 0
       0 3631.77   57.87 7976.61       0   57.27
Permanent Ineff=
       F       F
#Block Obstruct= 2 , 0
       0 1903.41   59.13 8177.46       0   57.52
Bank Sta=4871.88,4912.64
XS Rating Curve= 0
Exp/Cntr=.3,.1

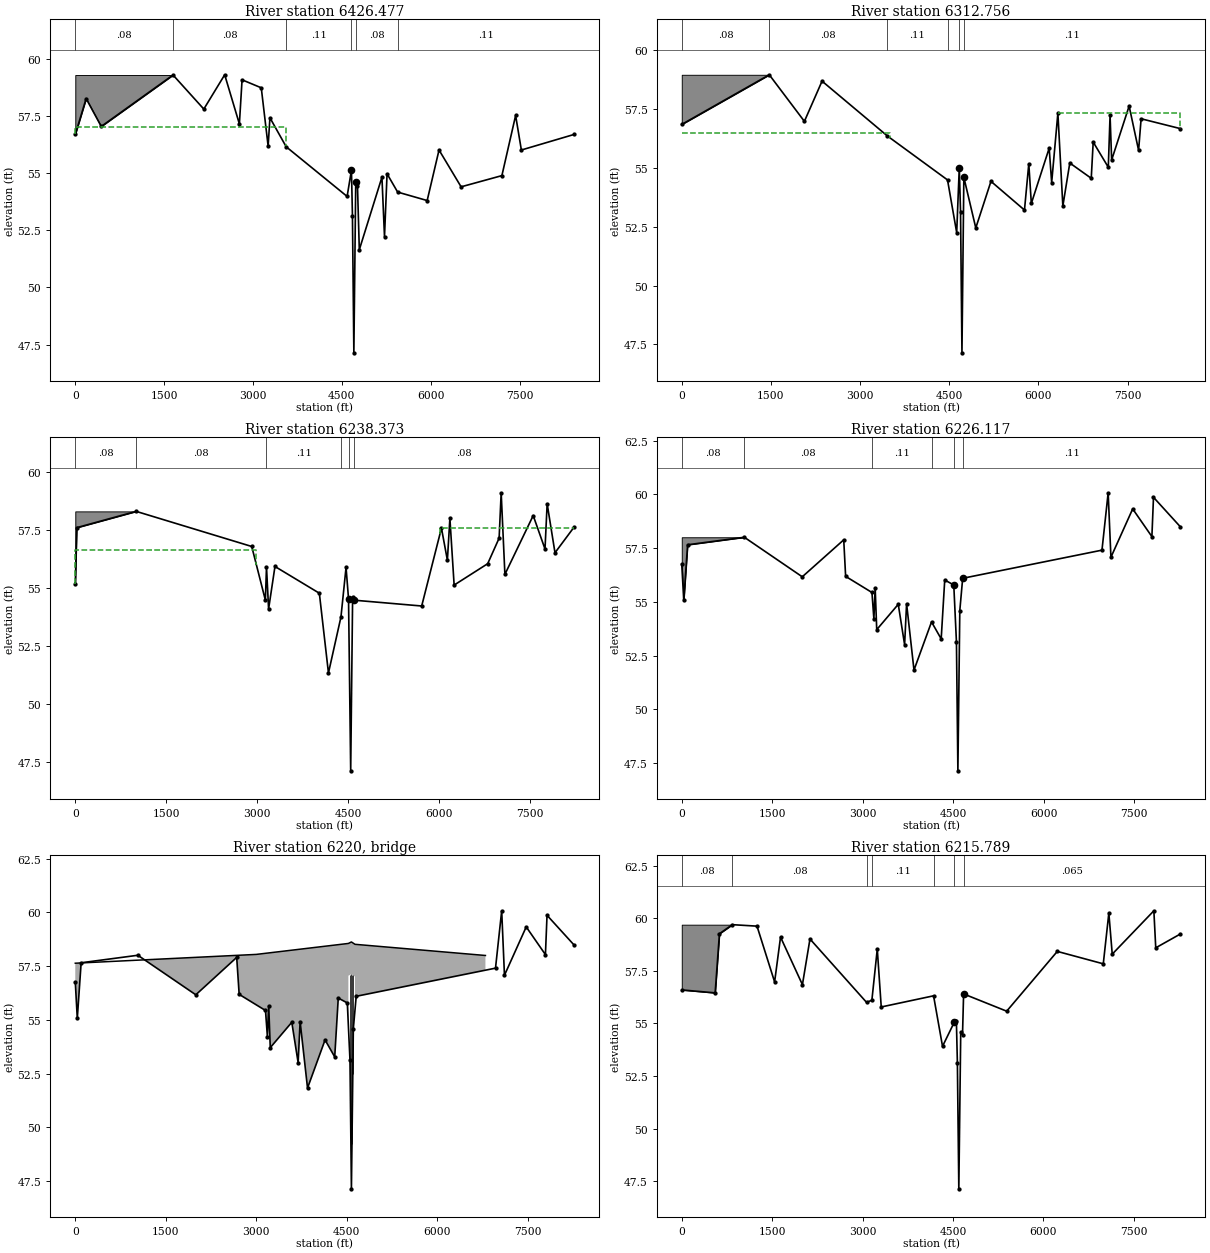
Type RM Length L Ch R = 1 ,6426.477,113.72,113.72,113.72
XS GIS Cut Line= 6
     3236217.504    13923463.329     3234870.704    13920579.494
     3234778.478    13919853.857     3234687.066    13919134.616
     3234591.444    13919055.054      3231967.92    13916509.476
#Sta/Elev= 30
       0   56.69  183.04   58.26  438.05   57.04 1649.98   59.29 2169.81    57.8
 2522.03    59.3 2770.17   57.15 2815.46   59.08 3139.59   58.73 3255.55   56.18
 3285.79   57.42 3560.73   56.15  4588.9   53.98 4662.07   55.13 4678.76   53.14
 4702.68   47.14 4734.47    54.6 4763.72   54.45 4794.72   51.65  5176.6   54.82
 5219.96   52.22 5263.04   54.97  5441.8   54.17 5940.36    53.8 6140.51   56.01
 6513.19    54.4 7201.68   54.89 7433.58   57.52 7530.33   56.01 8419.24   56.69
#Mann= 6 ,-1 , 0
       0     .08       0 1649.98     .08       0 3560.73     .11       0
 4662.07     .05       0 4734.47     .08       0  5441.8     .11       0
#XS Ineff= 2 , 0
       0  3550.5   57.03 6140.51       0   56.01
Permanent Ineff=
       F       F
#Block Obstruct= 2 , 0
       0 1649.98   59.29 7433.58       0   57.52
Bank Sta=4662.07,4734.47
XS Rating Curve= 0
Exp/Cntr=.3,.1

Type RM Length L Ch R = 1 ,6312.756,74.38,74.38,74.38
BEGIN DESCRIPTION:
E
END DESCRIPTION:
XS GIS Cut Line= 6
     3236579.505     13923276.49     3234941.425     13920124.14
     3234754.035    13919042.627     3234658.413    13918963.065
     3233406.673    13917745.686     3232023.794    13916488.523
#Sta/Elev= 30
       0   56.85 1472.37   58.96 2063.01   56.98    2360   58.69 3458.78   56.36
 4470.83   54.49 4625.09   52.25 4668.55   55.01 4689.61   53.14 4713.53   47.14
 4745.31    54.6 4946.28   52.45 5201.57   54.43 5765.27   53.21 5838.03   55.18
 5880.46   53.49  6180.8   55.84 6222.65   54.38 6327.27   57.33 6410.71   53.38
 6527.53   55.21 6888.56   54.56 6921.18    56.1 7175.27   55.03 7204.99   57.23
 7231.77   55.34 7525.68   57.63 7684.96   55.75 7727.44   57.09 8389.58   56.67
#Mann= 6 ,-1 , 0
       0     .08       0 1472.37     .08       0 3458.78     .11       0
 4470.83     .08       0 4668.55     .05       0 4745.31     .11       0
#XS Ineff= 2 , 0
       0 3503.89   56.49 6327.27       0   57.33
Permanent Ineff=
       F       F
#Block Obstruct= 2 , 0
       0 1472.37   58.96 6327.27       0   57.33
Bank Sta=4668.55,4745.31
XS Rating Curve= 0
Exp/Cntr=.3,.1

Type RM Length L Ch R = 1 ,6238.373,12.26,12.26,12.26
XS GIS Cut Line= 6
     3237942.237    13922182.403     3235079.447    13919393.934
     3234821.839    13919048.934     3234811.981    13918994.283
     3234105.942    13918366.043     3232071.875     13916438.16
#Sta/Elev= 30
       0   55.17   23.87    57.6 1005.64    58.3  2912.8   56.79 3138.07   54.48
 3156.54   55.91 3191.15    54.1 3296.26   55.93 4028.92   54.78 4179.35   51.35
 4385.81   53.76 4469.77   55.89 4510.74   54.54  4546.4   47.14 4578.19    54.6
  4602.7   54.48 5718.55   54.23 6044.75   57.58 6142.62    56.2 6184.05      58
 6254.02   55.13 6808.23   56.05 6996.83   57.15 7030.65    59.1 7092.14   55.59
 7559.19   58.12  7754.2   56.68 7789.64   58.63 7919.12   56.52 8233.08   57.62
#Mann= 6 ,-1 , 0
       0     .08       0 1005.64     .08       0 3156.54     .11       0
 4385.81     .08       0 4510.74     .05       0  4602.7     .08       0
#XS Ineff= 2 , 0
       0 2989.21   56.63  6019.6       0   57.58
Permanent Ineff=
       F       F
#Block Obstruct= 2 , 0
       0 1005.64    58.3 7026.55       0   59.02
Bank Sta=4510.74,4602.7
XS Rating Curve= 0
Exp/Cntr=.5,.3

Type RM Length L Ch R = 1 ,6226.117,30,30,30
XS GIS Cut Line= 6
     3237999.407    13922175.257     3236017.036    13920191.456
     3235373.873    13919639.766     3234821.151    13918986.002
     3234116.867    13918359.488     3232079.376    13916428.366
#Sta/Elev= 30
       0   56.76   33.28   55.07   97.01   57.66 1037.38   58.01 1998.16   56.17
 2685.57   57.89 2716.96   56.19 3153.51   55.44 3185.44   54.21 3206.73   55.66
 3232.63   53.71 3589.54   54.89  3694.9   53.01 3727.62   54.92 3850.41   51.83
 4141.22   54.07 4301.32   53.28 4360.06   56.02 4510.05   55.79 4554.25   53.14
 4578.17   47.14 4609.96    54.6 4657.58    56.1 6967.09   57.41 7069.71   60.08
 7115.65   57.08 7476.37   59.33  7794.8   58.04 7821.35   59.87 8268.76   58.49
#Mann= 6 ,-1 , 0
       0     .08       0 1037.38     .08       0 3153.51     .11       0
 4141.22     .08       0 4510.05     .05       0 4657.58     .11       0
#XS Ineff= 2 , 0
       0 4510.05   55.79 4657.58       0    56.1
Permanent Ineff=
       F       F
#Block Obstruct= 2 , 0
       0 1037.37   58.01 7069.71       0   60.08
Bank Sta=4510.05,4657.58
XS Rating Curve= 0
Exp/Cntr=.5,.3

Type RM Length L Ch R = 3 ,6220    ,,,
BEGIN DESCRIPTION:
RR BRIDGE
END DESCRIPTION:
Bridge Culvert--1,0,-1,-1, 0
Deck Dist Width WeirC Skew NumUp NumDn MinLoCord MaxHiCord MaxSubmerge Is_Ogee
10,10,2.6,0, 6, 6, , , .95, 0, 0,0,,
       0    3000    4528    4578    4637    6800
   57.64   58.05   58.56   58.63   58.52      58
                   57.06   57.13   57.02
    2100    3000    4528    4578    4637    7200
      58   58.05   58.56   58.63   58.52      58
                   57.06   57.13   57.02
Pier Skew, UpSta & Num, DnSta & Num=  ,4558, 4 ,4558, 4 , 3 , 3 , 0 ,,
    1.25    1.25     1.5     1.5
      50   55.56   55.56      58
    1.25    1.25     1.5     1.5
      50   55.56   55.56      58
Pier Skew, UpSta & Num, DnSta & Num=  ,4572, 4 ,4572, 4 , 3 , 3 , 0 ,,
    1.25    1.25     1.5     1.5
      45   55.56   55.56      58
    1.25    1.25     1.5     1.5
      45   55.56   55.56      58
Pier Skew, UpSta & Num, DnSta & Num=  ,4587, 4 ,4587, 4 , 3 , 3 , 0 ,,
    1.25    1.25     1.5     1.5
      45   55.56   55.56      58
    1.25    1.25     1.5     1.5
      45   55.56   55.56      58
Pier Skew, UpSta & Num, DnSta & Num=  ,4601, 4 ,4601, 4 , 3 , 3 , 0 ,,
    1.25    1.25     1.5     1.5
      50   55.56   55.56      58
    1.25    1.25     1.5     1.5
      50   55.56   55.56      58
BR Coef=-1 , 1 , 1 ,1.05, 0 ,,,.8,-1,1.2,0,
WSPro=,,,, 1 ,,,, 0 ,,,, 0 ,,,,-1 ,-1 ,-1 , 0 , 0 , 0 , 0 , 0
BR U #Sta/Elev= 30
       0   56.76   33.28   55.07   97.01   57.66 1037.38   58.01 1998.16   56.17
 2676.06   57.91 2716.96   56.19 3153.51   55.44 3185.44   54.21 3206.73   55.66
 3232.63   53.71 3589.54   54.89  3694.9   53.01 3727.62   54.92 3850.41   51.83
 4141.22   54.07 4301.32   53.28 4360.06   56.02 4510.05   55.79 4554.25   53.14
 4578.17   47.14 4609.96    54.6 4657.58    56.1 6967.09   57.41 7069.71   60.08
 7115.65   57.08 7476.37   59.33  7794.8   58.04 7821.35   59.87 8268.76   58.49
BR U #Mann= 6
       0     .08 1037.38     .08 3153.51     .11 4141.22     .08 4510.05    .049
 4657.58     .11
BR D #Sta/Elev= 30
       0   56.59  554.01   56.45  625.11   59.26  838.96   59.69 1248.19   59.62
 1540.24   56.97 1638.52    59.1 2001.61   56.84 2126.75   59.01 3064.96      56
 3153.67    56.1 3243.13   58.53 3308.91   55.78    4177   56.31 4325.49   53.91
 4521.12   55.06 4555.21   55.13 4571.91   53.14 4595.83   47.14 4627.62    54.6
 4657.12   54.47  4675.2    56.4 5389.69   55.58 6229.22   58.42 6992.03   57.83
  7084.3   60.24 7140.61   58.29 7831.12   60.35 7862.26   58.59 8272.58   59.25
BR D #Mann= 7
       0     .08  838.96     .08 3064.96     .08 3153.67     .11    4177    .065
 4521.12    .049  4675.2    .065
BC Design=,, 0 ,, 0 ,,,,,,

Type RM Length L Ch R = 1 ,6215.789,10.21,10.21,10.21
XS GIS Cut Line= 6
     3238058.006    13922153.818     3237655.821    13921711.466
     3236001.314    13920078.546     3234827.265    13918977.684
     3234487.607    13918682.155     3232100.445    13916422.124
#Sta/Elev= 30
       0   56.59  554.01   56.45  625.11   59.26  838.96   59.69 1248.19   59.62
 1540.24   56.97 1638.52    59.1 2001.61   56.84 2126.75   59.01 3064.96      56
 3153.67    56.1 3243.13   58.53 3308.91   55.78    4177   56.31 4325.49   53.91
 4521.12   55.06 4555.21   55.13 4571.91   53.14 4595.83   47.14 4627.62    54.6
 4657.12   54.47  4675.2    56.4 5389.69   55.58 6229.22   58.42 6992.03   57.83
  7084.3   60.24 7140.61   58.29 7831.12   60.35 7862.26   58.59 8272.58   59.25
#Mann= 7 ,-1 , 0
       0     .08       0  838.96     .08       0 3064.96     .08       0
 3153.67     .11       0    4177    .065       0 4521.12     .05       0
  4675.2    .065       0
#XS Ineff= 2 , 0
       0 4521.12   55.06  4675.2       0    56.4
Permanent Ineff=
       F       F
#Block Obstruct= 2 , 0
       0  838.96   59.69               0
Bank Sta=4521.12,4675.2
XS Rating Curve= 0
Exp/Cntr=.5,.3