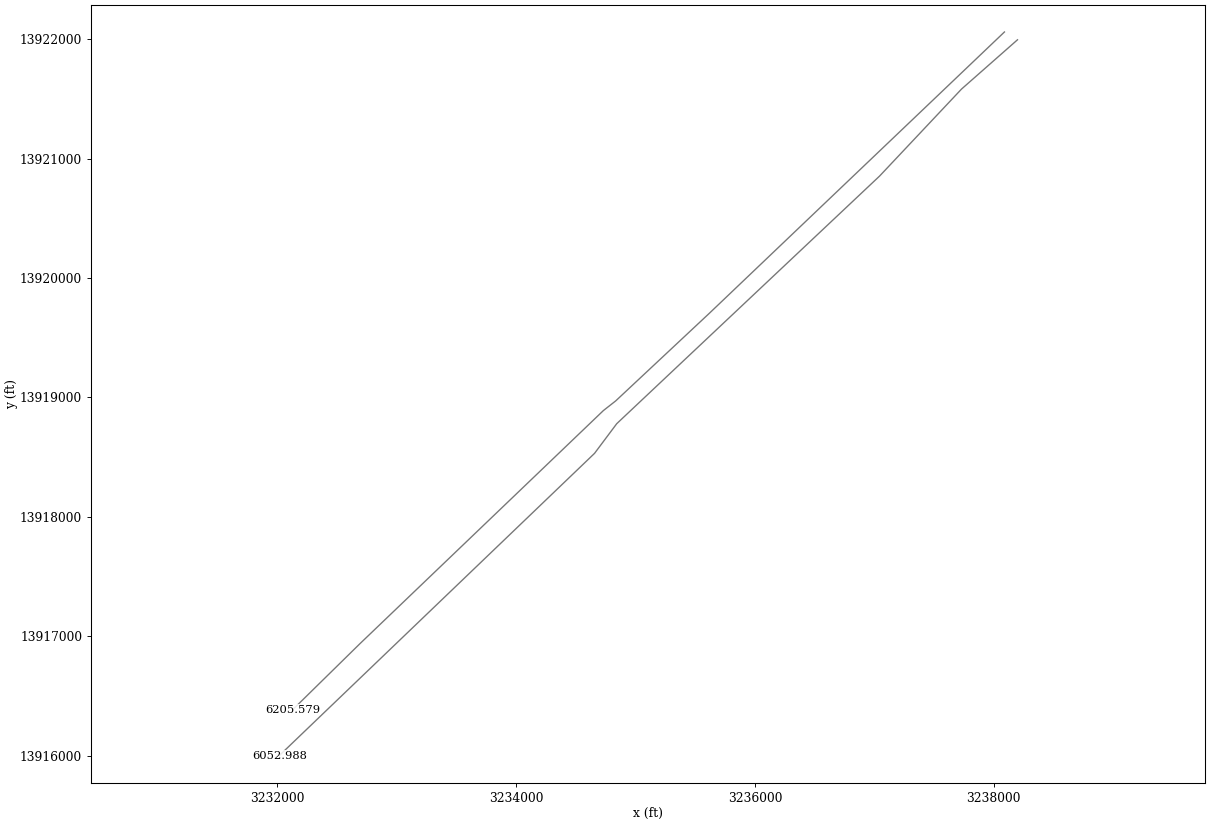
HEC-RAS study Q130-00-00.prj: Q130-00-00

--- Q130-00-00.g02 (geometry) --- (continued)

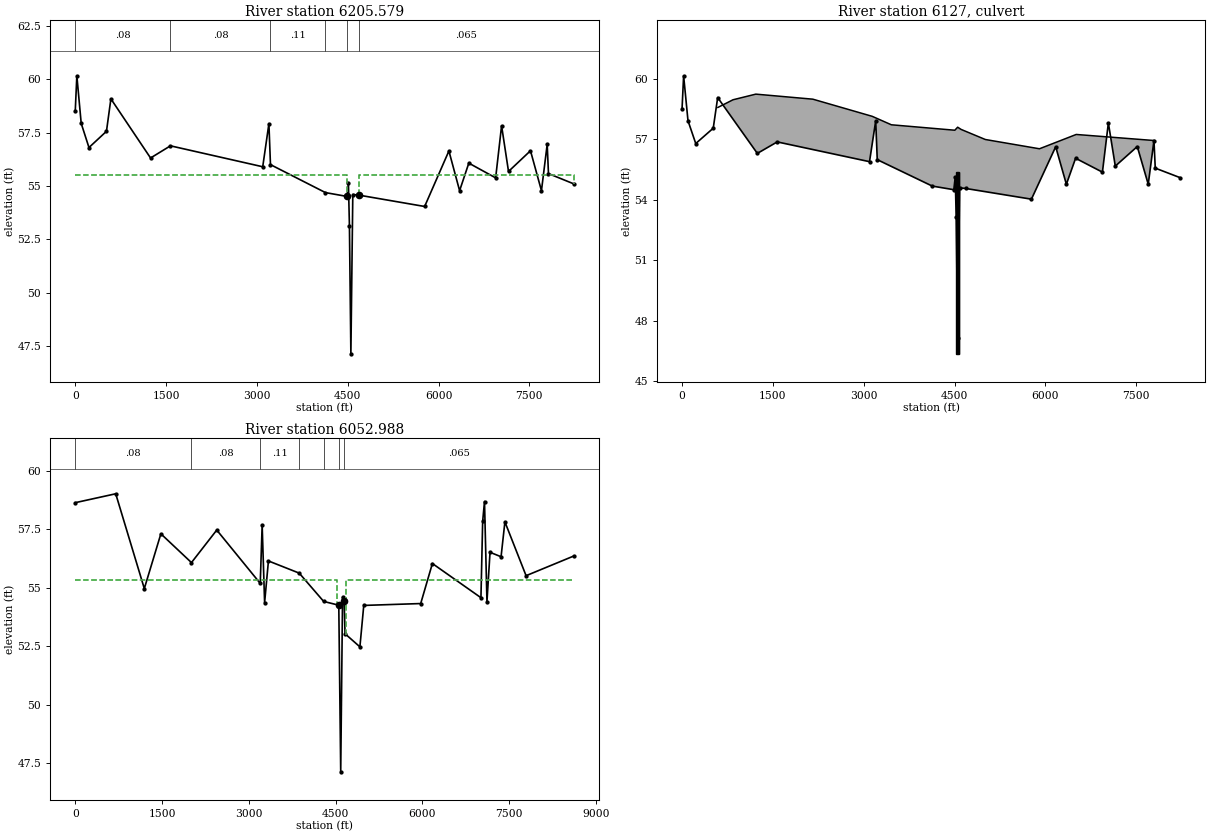
Type RM Length L Ch R = 1 ,6205.579,152.52,152.59,152.59
XS GIS Cut Line= 6
     3238089.554    13922059.695     3235619.808    13919705.318
     3234833.782    13918969.852     3234730.865    13918889.045
     3232691.672     13916936.43     3232129.029    13916384.134
#Sta/Elev= 30
       0   58.53   25.88   60.16   98.02   57.93  226.05    56.8  515.09   57.56
  588.25   59.08 1243.42   56.31 1571.86   56.88 3096.13    55.9  3198.2   57.92
 3223.93      56 4132.06   54.69 4488.66   54.51  4511.4   55.13  4528.1   53.14
 4552.02   47.14  4583.8    54.6 4687.01   54.57 5770.29   54.04 6171.08   56.64
  6347.7   54.78 6499.94   56.07 6943.05   55.38 7041.18   57.82 7155.59   55.68
 7518.59   56.65 7699.67   54.78 7794.37   56.95 7815.59   55.58 8232.44    55.1
#Mann= 6 ,-1 , 0
       0     .08       0 1571.86     .08       0 3223.93     .11       0
 4132.06     .08       0 4488.66     .05       0 4687.01    .065       0
#XS Ineff= 2 , 0
       0 4488.66   55.52 4684.47       0   55.52
Permanent Ineff=
       F       F
#Block Obstruct= 2 , 0
       0                 7041.18       0   57.82
Bank Sta=4488.66,4687.01
XS Rating Curve= 0
Exp/Cntr=.5,.3

Type RM Length L Ch R = 2 ,6127    ,,,
BEGIN DESCRIPTION:
US 90A WB
END DESCRIPTION:
Bridge Culvert--1,0,-1,-1, 0
Deck Dist Width WeirC Skew NumUp NumDn MinLoCord MaxHiCord MaxSubmerge Is_Ogee
37,83,2.6,0, 13, 13, , , .95, 0, 0,0,,
     592     841    1218    2160    3140    3457    4505    4552    4609    5009
    5903    6510 7794.37
   58.59   58.97   59.25      59   58.15   57.73   57.46   57.61    57.5      57
   56.54   57.25   56.95
                                                                                
                        
     592     841    1218    2160    3140    3457    4520    4592    4655    5009
    5903    6510    7433
   58.59   58.97   59.25      59   58.15   57.73   57.46   57.61    57.5      57
   56.54   57.25    57.8
                                                                                
                        
Multiple Barrel Culv=2,9,9,83,.013,.2,1,58,1,46.37,46.07, 5,Culvert #1  , 0 ,37
    4531    4567    4542    4577    4552    4589    4563    4600    4574    4610
Culvert Bottom n=.013
BC Design=,, 0 ,, 0 ,,,,,,

Type RM Length L Ch R = 1 ,6052.988,123.17,123.17,123.17
XS GIS Cut Line= 6
     3238198.942    13921994.343     3237730.294    13921581.668
     3237043.878    13920852.909     3234842.576    13918779.087
     3234656.654     13918530.58      3232016.81    13915999.627
#Sta/Elev= 30
       0   58.64  699.26   59.02 1193.81   54.97 1480.13   57.31  2008.9   56.08
 2446.41   57.47 3198.41   55.19  3231.4   57.68 3273.85   54.37 3340.01   56.15
 3872.27   55.63 4295.32   54.42 4556.52   54.26 4589.81   47.14 4621.59    54.6
 4649.17   54.46 4664.42   53.04 4921.61   52.48 4988.36   54.25 5972.94   54.33
 6174.93   56.04 7014.52   54.58 7044.32   57.84 7076.14   58.69 7118.57   54.41
 7171.61   56.52 7362.55   56.33 7428.77   57.82  7795.1   55.52 8618.66   56.36
#Mann= 7 ,-1 , 0
       0     .08       0  2008.9     .08       0 3198.41     .11       0
 3872.27     .08       0 4295.32    .065       0 4556.52     .05       0
 4649.17    .065       0
#XS Ineff= 2 , 0
       0    4520   55.35    4688       0   55.35
Permanent Ineff=
       F       F
#Block Obstruct= 2 , 0
       0                 7076.14       0   58.69
Bank Sta=4556.52,4649.17
XS Rating Curve= 0
Exp/Cntr=.5,.3