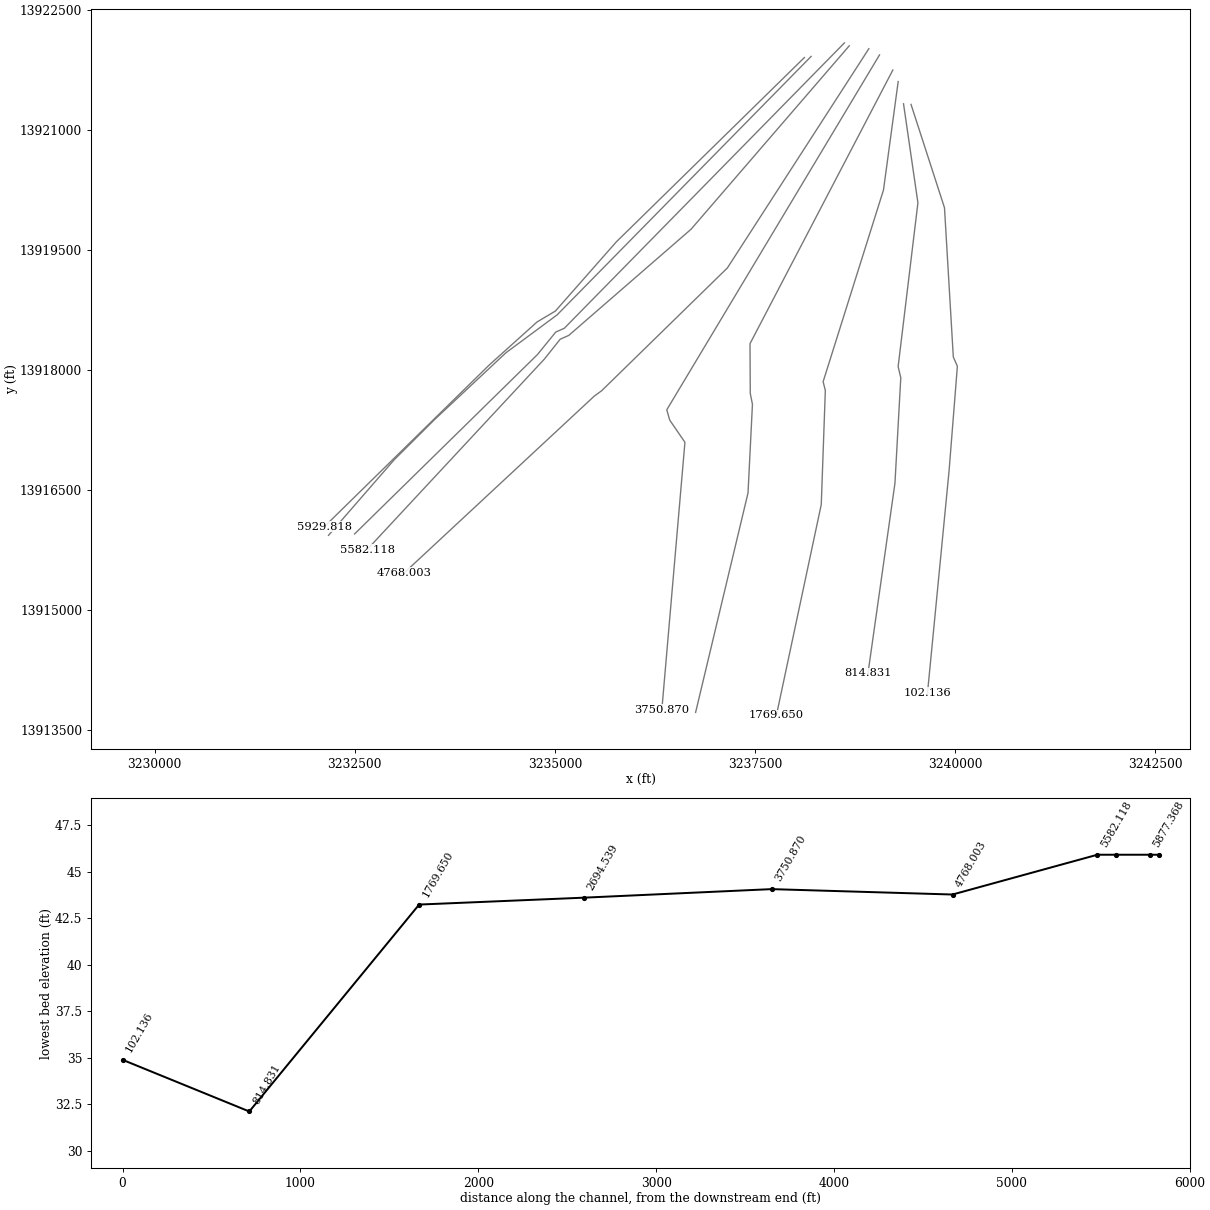
HEC-RAS study Q130-00-00.prj: Q130-00-00

--- Q130-00-00.g02 (geometry) --- (continued)

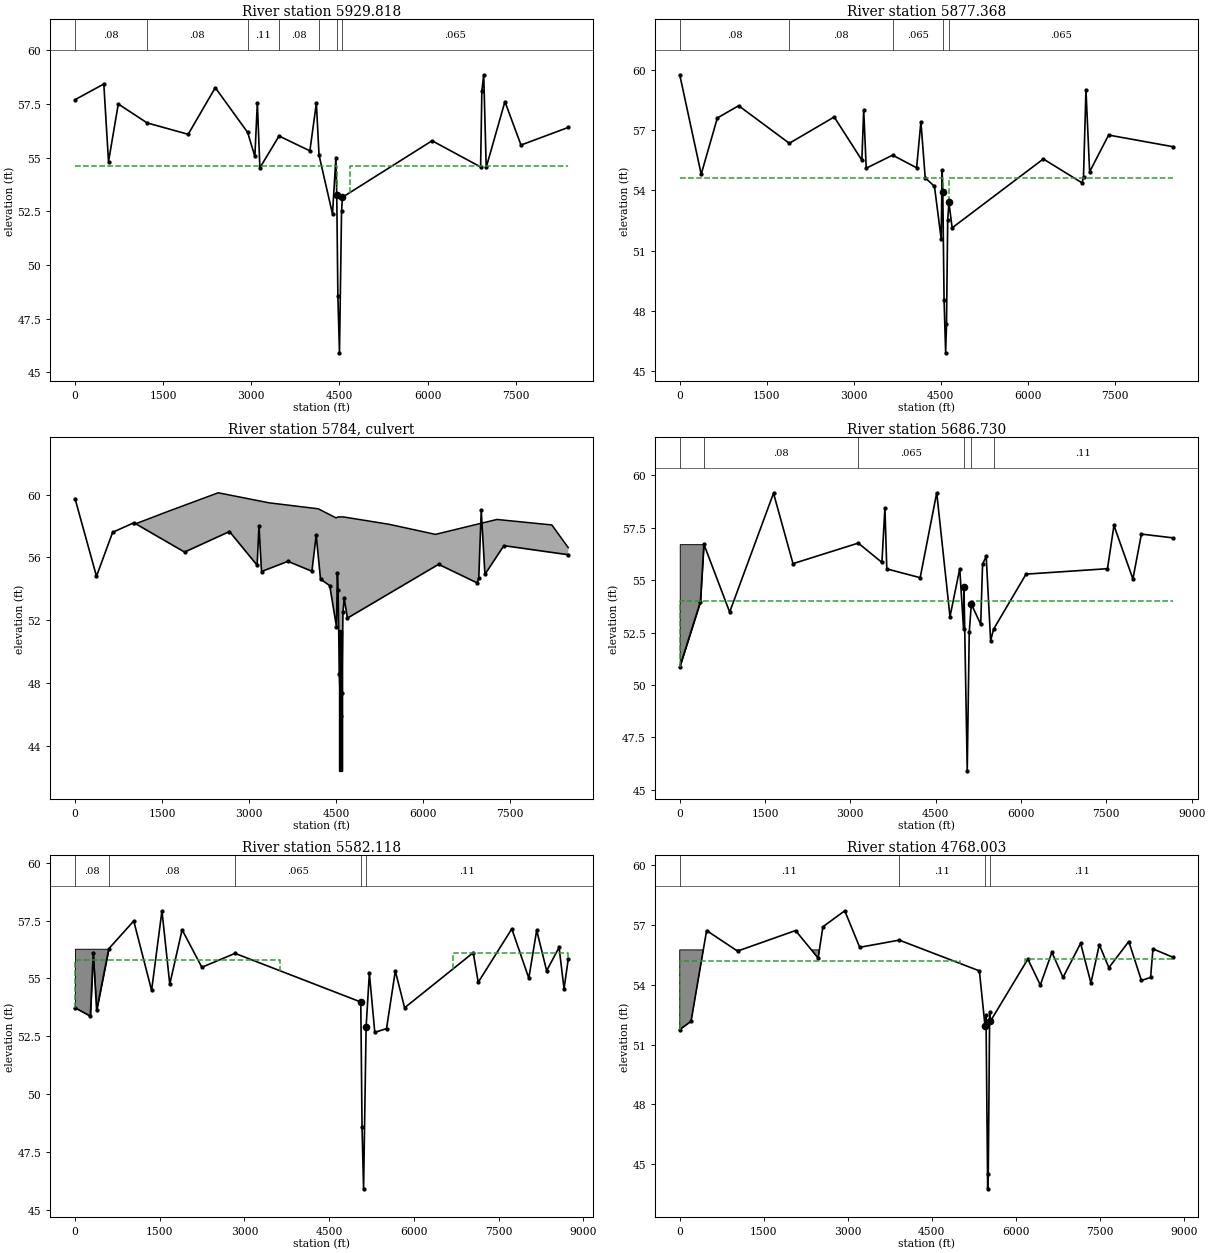
Type RM Length L Ch R = 1 ,5929.818,52.45,52.45,52.45
XS GIS Cut Line= 6
     3238115.366    13921901.049     3235767.189    13919599.618
      3235005.55    13918734.859     3234776.682    13918598.595
     3234180.547    13918062.474     3232120.082    13916042.018
#Sta/Elev= 30
       0   57.69  489.93   58.42  570.11   54.81  736.51   57.49 1226.78   56.61
 1926.04   56.08 2387.35   58.25 2937.85   56.17 3061.23   55.05  3103.4   57.55
 3146.79   54.52 3472.56      56 3997.45   55.31 4108.01   57.53  4153.4   55.11
 4382.76   52.37 4440.51      55    4455   53.25 4474.05   48.56 4501.34   45.91
 4536.68   52.51 4551.89   53.15 6077.25   55.78  6903.6   54.56 6924.81    58.1
 6956.63   58.85 6999.06   54.54 7317.26    57.6 7590.91   55.58 8395.99    56.4
#Mann= 7 ,-1 , 0
       0     .08       0 1226.78     .08       0 2937.85     .11       0
 3472.56     .08       0  4153.4    .065       0    4455     .05       0
 4551.89    .065       0
#XS Ineff= 2 , 0
       0 4452.25   54.59 4672.91       0   54.59
Permanent Ineff=
       F       F
#Block Obstruct= 2 , 0
       0                 6956.63       0   58.85
Bank Sta=4455,4551.89
XS Rating Curve= 0
Exp/Cntr=.5,.3

Type RM Length L Ch R = 1 ,5877.368,190.64,190.64,190.64
XS GIS Cut Line= 6
     3238199.787    13921915.376      3235027.81     13918687.76
     3234388.594    13918214.508     3233499.962    13917382.772
     3232992.546    13916877.959     3232172.093    13915933.994
#Sta/Elev= 30
       0   59.75  370.18    54.8   648.8    57.6 1015.58   58.21 1889.89   56.34
 2664.12   57.65 3141.44    55.5 3172.94   58.01 3216.39    55.1 3671.79   55.75
 4085.46   55.12 4159.71   57.41 4233.96   54.62 4393.07    54.2 4509.43   51.58
 4525.36      55  4537.1   53.93 4558.91   48.56 4586.19   45.91 4600.92   47.33
 4621.53   52.51 4642.69    53.4 4698.07   52.13 6271.18   55.56  6938.8   54.37
 6963.88   54.67  7006.2   59.01 7069.67   54.92 7396.88   56.75 8507.64   56.17
#Mann= 5 ,-1 , 0
       0     .08       0 1889.89     .08       0 3671.79    .065       0
  4537.1     .05       0 4642.69    .065       0
#XS Ineff= 2 , 0
       0    4536   54.59 4642.59       0   54.59
Permanent Ineff=
       F       F
#Block Obstruct= 2 , 0
       0                 7023.88       0   59.01
Bank Sta=4537.1,4642.69
XS Rating Curve= 0
Exp/Cntr=.5,.3

Type RM Length L Ch R = 2 ,5784    ,,,
BEGIN DESCRIPTION:
US90A EB
END DESCRIPTION:
Bridge Culvert--1,0,-1,-1, 0
Deck Dist Width WeirC Skew NumUp NumDn MinLoCord MaxHiCord MaxSubmerge Is_Ogee
40,106,2.6,0, 14, 13, , , .95, 0, 0,0,,
 1006.73    1601    2470    3348    4195    4502    4536    4584    4632    5420
    6216    7277    8224 8507.64
   58.09   58.93   60.12   59.48    59.1   58.52   58.58   58.58   58.58   58.11
   57.47   58.42   58.07   56.62
                                                                                
                                
    1601    2470    3348    4195    4502    4954    5037    5119    5420    6216
    7277    8224  8672.3
   58.93   60.12   59.48    59.1   58.52   58.58   58.58   58.48   58.11   57.47
   58.42   58.07   55.53
                                                                                
                        
Multiple Barrel Culv=2,9,9,106,.013,.2,1,58,1,42.4,41.85, 5,Culvert #1  , 0 ,40
    4561    5031    4572    5042    4584    5054    4596    5064    4606    5076
Culvert Bottom n=.013
BC Design=,, 0 ,, 0 ,,,,,,

Type RM Length L Ch R = 1 ,5686.730,104.61,104.61,104.61
XS GIS Cut Line= 6
     3238615.224    13922084.074     3235117.164    13918520.218
     3235048.153    13918489.463     3235009.998    13918472.458
     3234781.977    13918191.955     3232497.901    13915951.122
#Sta/Elev= 30
       0   50.86   363.9   53.98  424.55   56.72  877.83   53.48 1648.72   59.15
 1991.34   55.79  3138.6   56.77 3554.51   55.85 3607.56   58.46 3640.19   55.54
  4227.1   55.12 4518.15   59.17 4751.46   53.26 4922.83   55.55 4989.25   52.68
 4997.24   54.68 5054.58   45.91 5089.92   52.51 5126.42   53.86 5291.64    52.9
 5324.19   55.77    5388   56.14 5465.61   52.12 5518.58   52.67 6088.67   55.29
 7520.19   55.55 7634.28   57.61 7967.31   55.06 8116.67    57.2  8672.3   57.02
#Mann= 6 ,-1 , 0
       0     .08       0  424.55     .08       0  3138.6    .065       0
 4997.24     .04       0 5126.42    .065       0 5518.58     .11       0
#XS Ineff= 2 , 0
       0    4954      54 5126.42       0      54
Permanent Ineff=
       F       F
#Block Obstruct= 2 , 0
       0  424.55   56.72 6788.13       0   55.61
Bank Sta=4997.24,5126.42
XS Rating Curve= 0
Exp/Cntr=.5,.3

Type RM Length L Ch R = 1 ,5582.118,814.11,814.11,814.11
BEGIN DESCRIPTION:
D
END DESCRIPTION:
XS GIS Cut Line= 6
     3238675.821    13922047.716     3236700.375    13919757.169
     3235172.972    13918431.018     3235065.805    13918383.257
     3234868.399    13918135.545     3232654.187    13915755.766
#Sta/Elev= 30
       0   53.73   271.2   53.37  322.32   56.09  382.66   53.62  597.93   56.28
 1039.35   57.48 1355.85   54.48  1538.9   57.92  1677.4   54.75 1895.79    57.1
 2244.95   55.48 2833.14   56.08  5058.7   53.98 5081.06   48.56 5108.34   45.91
 5153.18   52.91 5210.76   55.22 5306.66   52.67 5514.33   52.83 5670.12   55.32
  5834.6   53.73 7049.58   56.11 7137.66   54.83 7732.22   57.14 8033.24   55.01
 8172.63   57.08  8348.8   55.33    8569   56.34 8657.08   54.55 8732.14   55.85
#Mann= 5 ,-1 , 0
       0     .08       0  597.93     .08       0 2833.14    .065       0
  5058.7     .04       0 5153.18     .11       0
#XS Ineff= 2 , 0
       0 3632.11    55.8 6699.54       0   56.11
Permanent Ineff=
       F       F
#Block Obstruct= 2 , 0
       0  597.93   56.28 6983.51       0   55.69
Bank Sta=5058.7,5153.18
XS Rating Curve= 0
Exp/Cntr=.3,.1

Type RM Length L Ch R = 1 ,4768.003,934,1017.13,1182
XS GIS Cut Line= 6
     3238920.619      13922011.7     3237153.635    13919273.429
     3235583.659    13917740.057     3235536.926    13917706.045
     3235492.057    13917673.388     3233116.971    13915464.563
#Sta/Elev= 30
       0   51.75  202.01   52.16  480.09   56.71 1032.08   55.68 2068.54   56.71
 2471.95   55.33 2557.26    56.9 2947.42    57.7 3214.48   55.87 3920.51   56.23
 5351.65   54.69 5453.15   51.92 5470.32   52.46 5499.77   43.77 5510.54   44.53
 5535.58   52.63 5549.71   52.17 6217.78   55.28 6440.32   53.98 6647.54   55.62
 6845.77   54.36 7160.05   56.07  7344.4   54.08 7493.75      56 7664.73   54.85
 8020.38   56.16 8245.71   54.21 8409.58   54.36 8452.05   55.79 8810.17   55.37
#Mann= 4 ,-1 , 0
       0     .11       0 3920.51     .11       0 5453.15     .04       0
 5549.71     .11       0
#XS Ineff= 2 , 0
       0 5013.42   55.16  6173.1       0   55.28
Permanent Ineff=
       F       F
#Block Obstruct= 2 , 0
       0 3898.44   55.74 7160.05       0   56.07
Bank Sta=5453.15,5549.71
XS Rating Curve= 0
Exp/Cntr=.3,.1

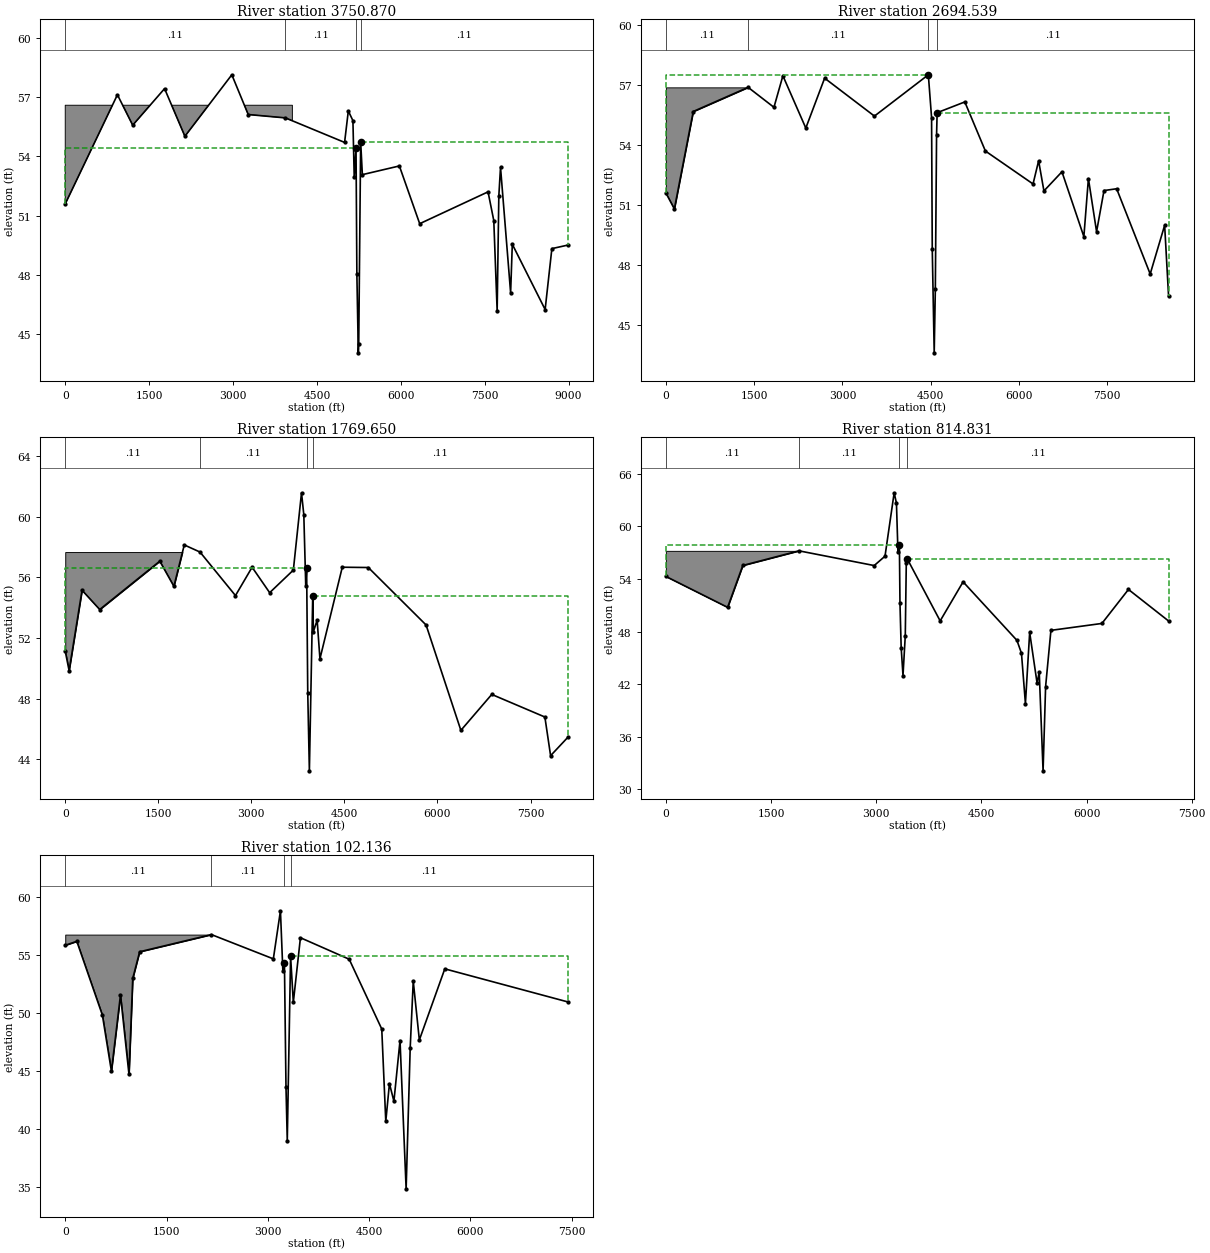
Type RM Length L Ch R = 1 ,3750.870,1056.33,1056.33,1056.33
BEGIN DESCRIPTION:
C
END DESCRIPTION:
XS GIS Cut Line= 6
     3239053.781    13921934.022     3236396.703    13917501.622
      3236415.12    13917437.501     3236433.603    13917373.157
     3236623.573    13917095.799     3236335.055    13913755.649
#Sta/Elev= 30
       0   51.59  933.15   57.11  1206.5   55.57 1776.32   57.42 2139.99   55.01
 2979.09   58.12 3272.35   56.11 3936.92   55.94 4995.46    54.7 5062.37   56.29
 5144.63    55.8  5167.8   52.94 5200.15   54.41 5215.16   48.05 5241.03   44.06
 5248.38    44.5  5283.1   54.73 5313.34   53.07 5975.25   53.51  6338.7   50.59
 7560.97    52.2 7663.61   50.75 7723.83   46.19 7753.94      52 7784.06   53.44
 7964.73    47.1 7994.84   49.55 8582.02   46.25 8702.46   49.33 8990.23   49.51
#Mann= 4 ,-1 , 0
       0     .11       0 3936.92     .11       0 5200.15     .04       0
  5283.1     .11       0
#XS Ineff= 2 , 0
       0 5200.15   54.41  5283.1       0   54.73
Permanent Ineff=
       F       F
#Block Obstruct= 2 , 0
       0  4061.9   56.58  5525.7       0   54.27
Bank Sta=5200.15,5283.1
XS Rating Curve= 0
Exp/Cntr=.3,.1

Type RM Length L Ch R = 1 ,2694.539,924.89,924.89,924.89
XS GIS Cut Line= 6
     3239220.234    13921745.376      3237436.19     13918327.68
     3237439.492    13917705.789     3237466.675    13917570.346
     3237411.449    13916463.279     3236756.735    13913722.359
#Sta/Elev= 30
       0   51.61  144.42   50.81  465.16   55.69 1398.19    56.9 1836.49    55.9
  1988.6   57.48 2377.95   54.86 2697.67   57.36 3543.86   55.46 4459.74   57.53
 4514.85   55.38 4526.41   48.81 4559.63    43.6 4578.81   46.82 4599.71   54.51
 4609.26   55.63 5079.52   56.17 5429.37   53.71 6238.82   52.06 6333.64   53.22
 6423.89   51.71 6729.87   52.67 7102.46   49.42 7179.57   52.33 7318.36   49.67
 7444.53   51.73 7659.49   51.82 8229.25   47.55 8475.02   49.99 8541.83   46.44
#Mann= 4 ,-1 , 0
       0     .11       0 1398.19     .11       0 4459.74     .04       0
 4609.26     .11       0
#XS Ineff= 2 , 0
       0 4459.74   57.53 4609.26       0   55.63
Permanent Ineff=
       F       F
#Block Obstruct= 2 , 0
       0 1398.19    56.9 4840.25       0   56.62
Bank Sta=4459.74,4609.26
XS Rating Curve= 0
Exp/Cntr=.3,.1

Type RM Length L Ch R = 1 ,1769.650,954.82,954.82,954.82
BEGIN DESCRIPTION:
B
END DESCRIPTION:
XS GIS Cut Line= 6
     3239286.815    13921601.117     3239103.095    13920246.479
     3238349.351    13917852.604     3238376.977    13917743.526
     3238326.192    13916318.849     3237766.548    13913689.068
#Sta/Elev= 30
       0   51.12   62.44   49.84  271.23   55.14  555.64   53.87 1524.05   57.06
 1751.29    55.4 1918.73   58.13 2172.47   57.66 2743.98   54.79 3012.12   56.66
 3295.18   54.98 3676.88   56.47 3808.44   61.57 3845.59   60.12 3876.78   55.44
 3890.93   56.62 3909.04   48.38 3935.32   43.23  3989.3   54.75 4000.48   52.41
 4060.52   53.17 4105.55   50.62 4465.62   56.66 4885.51   56.64 5816.54   52.85
 6377.46    45.9 6875.27   48.27 7731.46   46.78 7823.63   44.23 8103.55   45.45
#Mann= 4 ,-1 , 0
       0     .11       0 2172.47     .11       0 3890.93     .04       0
  3989.3     .11       0
#XS Ineff= 2 , 0
       0 3890.93   56.62  3989.3       0   54.75
Permanent Ineff=
       F       F
#Block Obstruct= 2 , 0
       0 2172.47   57.66 4419.41       0   55.84
Bank Sta=3890.93,3989.3
XS Rating Curve= 0
Exp/Cntr=.3,.1

Type RM Length L Ch R = 1 ,814.831 ,712.7,712.7,712.7
XS GIS Cut Line= 6
     3239353.396    13921323.696     3239533.247    13920086.709
     3239286.172    13918041.056     3239319.305    13917902.284
     3239246.464    13916585.121     3238909.523     13914210.62
#Sta/Elev= 30
       0    54.3  880.86   50.77 1097.49   55.55 1899.23   57.22 2971.88   55.54
 3125.98   56.61  3256.6   63.85 3289.17   62.66 3310.61   57.05 3331.24   57.87
 3339.26   51.27 3356.39   46.18 3382.51   42.98 3415.09   47.55 3429.54   55.82
 3445.69   56.27 3912.55   49.22  4239.7   53.68 5007.56      47 5072.24   45.53
 5128.77   39.78 5189.37    47.9 5295.42    42.1 5325.72   43.41 5380.55    32.1
 5416.62   41.72 5492.38   48.14 6219.59   48.93 6598.35   52.81 7170.75   49.21
#Mann= 4 ,-1 , 0
       0     .11       0 1899.23     .11       0 3331.24     .04       0
 3445.69     .11       0
#XS Ineff= 2 , 0
       0 3331.24   57.87 3445.69       0   56.27
Permanent Ineff=
       F       F
#Block Obstruct= 2 , 0
       0 1899.23   57.22 3518.87       0   56.77
Bank Sta=3331.24,3445.69
XS Rating Curve= 0
Exp/Cntr=.3,.1

Type RM Length L Ch R = 1 ,102.136 ,102.14,102.14,102.14
BEGIN DESCRIPTION:
A
END DESCRIPTION:
XS GIS Cut Line= 6
     3239447.216    13921315.712     3239865.078    13920025.259
     3239975.264    13918161.844     3240026.049    13918045.258
     3239922.383    13916740.458     3239653.011    13913966.489
#Sta/Elev= 30
       0   55.85  171.41   56.19  550.12   49.84  684.01   45.01  818.16   51.56
  944.29   44.73 1000.12      53 1101.96   55.29 2165.74   56.77 3082.34   54.68
 3187.53   58.82 3223.09   53.67 3246.62   54.31  3269.7   43.62 3288.59   39.04
 3337.84    54.9 3378.26   50.94 3483.59    56.5 4205.86   54.65 4688.15   48.64
 4747.69   40.69 4802.08   43.94 4868.26   42.42 4958.68   47.65  5049.1   34.88
 5109.39   47.02  5154.6   52.76 5245.02    47.7 5621.79   53.82 7446.19   50.97
#Mann= 4 ,-1 , 0
       0     .11       0 2165.74     .11       0 3246.62     .04       0
 3337.84     .11       0
#XS Ineff= 2 , 0
       0 3246.62   54.31 3337.84       0    54.9
Permanent Ineff=
       F       F
#Block Obstruct= 2 , 0
       0 2165.74   56.77 3650.73       0   56.72
Bank Sta=3246.62,3337.84
XS Rating Curve= 0
Exp/Cntr=.3,.1

Chan Stop Cuts=-1